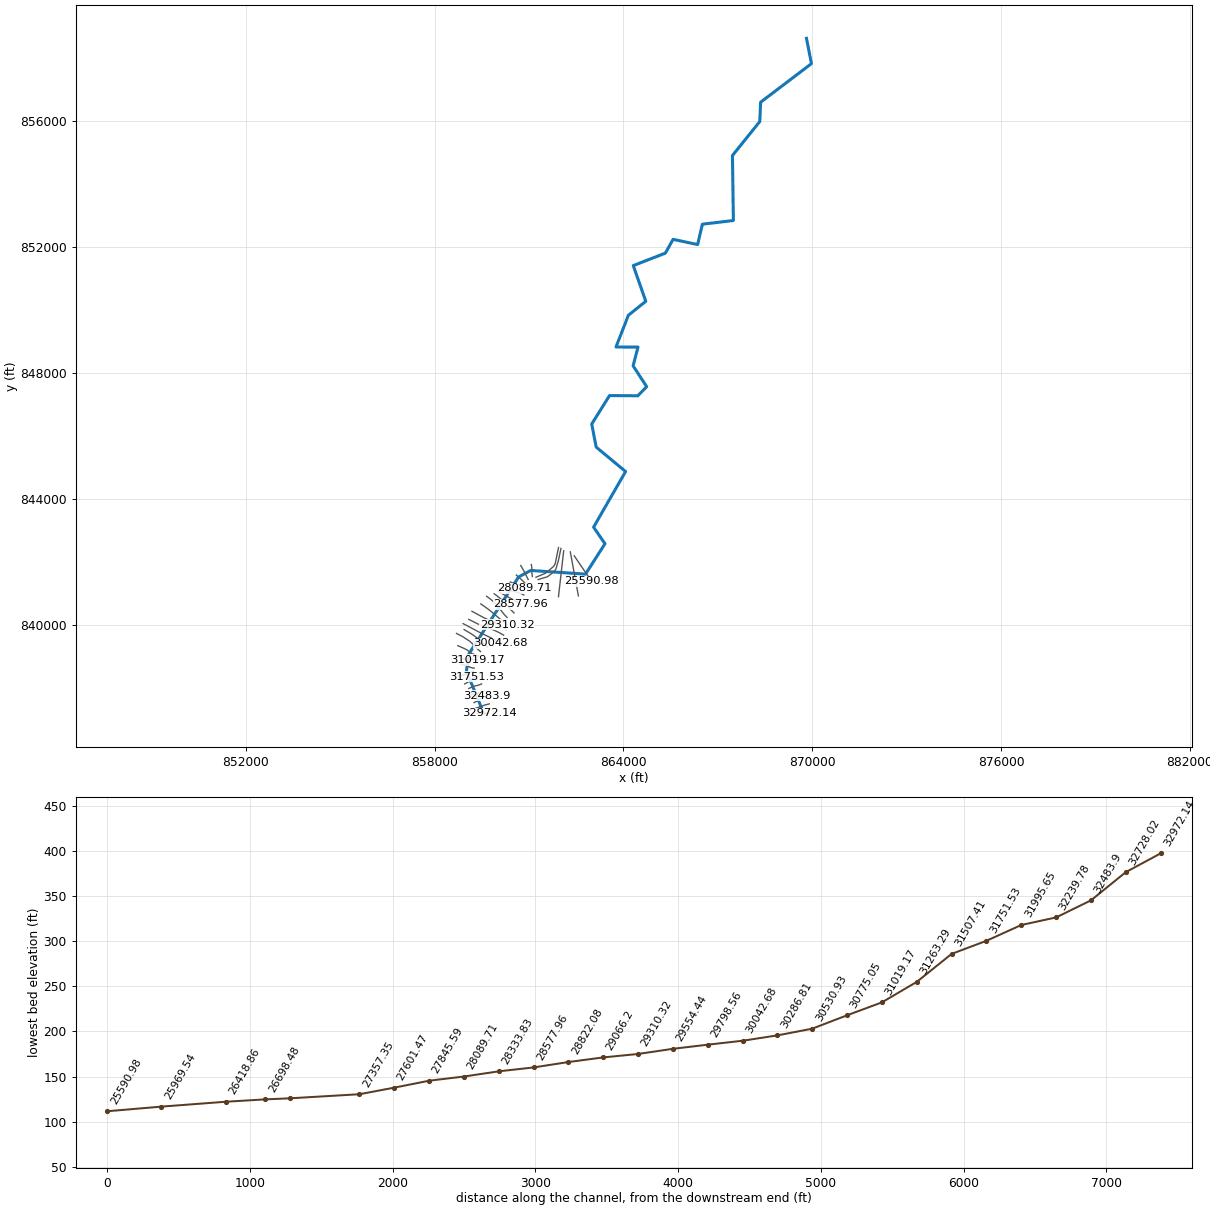
--- 16941_ras.prj (project) ---

Proj Title=16941
Current Plan=p01
Default Exp/Contr=0.3,0.1
English Units
Geom File=g01
Flow File=f01
Plan File=p01
Y Axis Title=Elevation
X Axis Title(PF)=Main Channel Distance
X Axis Title(XS)=Station
BEGIN DESCRIPTION:
RFD model 16941 exported to HEC-RAS
END DESCRIPTION:

--- 16941_ras.p01 (plan) ---

Plan Title=Plan 01
Program Version=4.10
Short Identifier=Plan 01
Geom File=g01
Flow File=f01
Subcritical Flow
Calc Critical at every XS
Secant Critical Depth

--- 16941_ras.f01 (steady flow) ---

Flow Title=Flow 01
Program Version=5.01
Number of Profiles= 6
Profile Names=10yr,25yr,50yr,100yr,100plus,500yr
River Rch & RM=16941,83,32972.14
10963.29 14418.717139.2719970.92 24729.726997.49
River Rch & RM=16941,83,32728.02
10978.7214439.9617165.3120002.0824768.2927041.95
River Rch & RM=16941,83, 32483.9
11055.1314545.2917294.3520156.5624959.5827262.38
River Rch & RM=16941,83,32239.78
11063.6314557.0117308.7120173.7524980.86 27286.9
River Rch & RM=16941,83,31995.65
11111.5614623.0917389.68 20270.725100.9127425.29
River Rch & RM=16941,83,31751.53
11123.1614639.0917409.2920294.1725129.9827458.81
River Rch & RM=16941,83,31507.41
11422.6515052.3917915.9620901.1225881.5528326.08
River Rch & RM=16941,83,31263.29
11440.5515077.1117946.2820937.4525926.5428378.04
River Rch & RM=16941,83,31019.17
11462.3515107.2217983.2120981.7125981.3528441.35
River Rch & RM=16941,83,30775.05
11477.1515127.6618008.2821011.7626018.5628484.33
River Rch & RM=16941,83,30530.93
11534.0515206.26 18104.721127.3326161.6728649.69
River Rch & RM=16941,83,30286.81
11545.7515222.4218124.5321151.1126191.11 28683.7
River Rch & RM=16941,83,30042.68
11799.1215572.6518554.3721666.5326829.3529421.77
River Rch & RM=16941,83,29798.56
11806.1715582.4118566.35 21680.926847.1529442.37
River Rch & RM=16941,83,29554.44
12468.0516499.0219692.71 23033.128521.5531383.29
River Rch & RM=16941,83,29310.32
12499.0116541.9619745.5223096.5528600.1231474.52
River Rch & RM=16941,83, 29066.2
12530.7916586.0319799.7223161.6828680.7831568.19
River Rch & RM=16941,83,28822.08
12540.3316599.2519815.9923181.2328704.9931596.31
River Rch & RM=16941,83,28577.96
12560.9916627.9219851.2623223.6128757.4631657.26
River Rch & RM=16941,83,28333.83
12580.08 16654.419883.8323262.7528805.9331713.56
River Rch & RM=16941,83,28089.71
12588.0316665.43 19897.423279.0628826.1331737.04
River Rch & RM=16941,83,27845.59
13148.3917443.6320855.4624431.1930252.7933396.71
River Rch & RM=16941,83,27601.47
13161.24 17461.520877.4724457.68 30285.633434.93
River Rch & RM=16941,83,27357.35
13178.9217486.0820907.7624494.1330330.72 33487.5
River Rch & RM=16941,83,26869.11
13203.0317519.6120949.0724543.8430392.2933559.23
River Rch & RM=16941,83,26698.48
13217.5117539.7320973.8724573.6830429.2433602.29
River Rch & RM=16941,83,26418.86
13229.5717556.5120994.5424598.5630460.0533638.19
River Rch & RM=16941,83,25969.54
14819.4719773.5723731.4727898.2134545.9538416.47
River Rch & RM=16941,83,25590.98
15298.1720443.3924560.2528899.4835785.8139872.81
River Rch & RM=16941,83,25214.73
15320.6220474.8224599.1628946.5235844.0539941.29
River Rch & RM=16941,83,24967.44
15397.9920583.1824733.3229108.6936044.8740177.45
River Rch & RM=16941,83,24720.15
15704.1521012.2525264.7529751.3336840.65   41114
River Rch & RM=16941,83,24334.26
 15728.421046.2525306.88 29802.336903.7541188.32
River Rch & RM=16941,83,23751.64
 15785.321126.0325405.7429921.8937051.8541362.76
River Rch & RM=16941,83, 23236.4
15882.4621262.3225574.6430126.25 37304.9 41660.9
River Rch & RM=16941,83, 22989.1
15890.8421274.0825589.2130143.8837326.7341686.64
River Rch & RM=16941,83,22741.81
   1591621309.3725632.9630196.8137392.2841763.88
River Rch & RM=16941,83,22494.52
16136.0621618.2126015.8430660.2437966.13 42440.5
River Rch & RM=16941,83,22247.23
16147.8321634.7426036.3430685.0637996.8642476.75
River Rch & RM=16941,83,21962.82
16168.0321663.0926071.5130727.6338049.5842538.93
River Rch & RM=16941,83,21600.93
 16201.721710.3726130.1330798.6138137.4742642.63
River Rch & RM=16941,83,21119.15
16223.5921741.1226168.2730844.7838194.6442710.09
River Rch & RM=16941,83,20763.48
16243.81 21769.526203.4830887.4138247.4442772.39
River Rch & RM=16941,83,20516.19
16256.4521787.2526225.4930914.0738280.4542811.34
River Rch & RM=16941,83,20268.89
16582.4322245.2826793.7831602.3839132.7743817.79
River Rch & RM=16941,83, 20021.6
16594.2822261.9426814.4531627.4339163.7943854.45
River Rch & RM=16941,83,19734.82
16623.92 22303.626866.1631690.0939241.3843946.12
River Rch & RM=16941,83,19434.64
16680.6822383.4126965.2331810.1239390.0144121.79
River Rch & RM=16941,83,18934.21
16994.9222825.4827514.1532475.4840213.9145096.18
River Rch & RM=16941,83, 18328.2
17739.8523874.96 28818.634058.0542173.5947418.18
River Rch & RM=16941,83,17756.43
17768.2123914.9628868.3634118.4542248.3847506.92
River Rch & RM=16941,83,   17356
18033.4424289.1629333.9234683.7842948.4248337.93
River Rch & RM=16941,83,16968.74
 18078.324352.4829412.73 34779.543066.9548478.71
River Rch & RM=16941,83,16554.15
18101.6124385.3829453.6734829.2343128.5348551.86
River Rch & RM=16941,83,16312.22
18110.2424397.5729468.8434847.6543151.3448578.96
River Rch & RM=16941,83, 16102.1
18194.0324515.8729616.0935026.5343372.8548842.13
River Rch & RM=16941,83,15813.48
 18457.224887.5930078.9135588.9144069.24   49670
River Rch & RM=16941,83,15494.82
18483.2224924.3530124.6935644.5544138.1449751.95
River Rch & RM=16941,83,14794.73
18517.9224973.3830185.7635718.7944230.0549861.28
River Rch & RM=16941,83,14307.33
18693.3825221.4130494.7136094.3844695.1450414.69
River Rch & RM=16941,83, 14086.6
18709.0425243.5430522.29 36127.944736.6650464.11
River Rch & RM=16941,83,13839.31
18729.0425271.8330557.5336170.7544789.7150527.27
River Rch & RM=16941,83,13592.01
18753.4125306.2830600.4636222.9444854.34 50604.2
River Rch & RM=16941,83,13344.72
 18776.925339.5130641.8636273.2944916.6950678.42
River Rch & RM=16941,83,12806.64
   1907625762.6231169.22 36914.745710.94 51624.5
River Rch & RM=16941,83,12392.48
19096.0925791.0631204.6736957.8345764.3551688.14
River Rch & RM=16941,83,12092.71
19124.0625830.6431254.0137017.8745838.6951776.75
River Rch & RM=16941,83,11613.68
19180.0225909.8431352.7737138.0245987.4851954.11
River Rch & RM=16941,83,11028.48
19228.1325977.9631437.7137241.3846115.4652106.68
River Rch & RM=16941,83,10560.07
19299.0526078.3631562.9237393.7446304.1352331.66
River Rch & RM=16941,83,10129.93
19407.7226232.2631754.8737627.3646593.4152676.72
River Rch & RM=16941,83,10014.65
19412.9826239.7131764.1637638.6846607.4352693.44
River Rch & RM=16941,83, 9808.75
19436.6626273.2631806.0137689.6146670.4952768.68
River Rch & RM=16941,83,9512.622
19461.2326308.0631849.4237742.4546735.9352846.75
River Rch & RM=16941,83,8984.959
19664.17 26595.632208.1838179.2247276.7853492.29
River Rch & RM=16941,83,8260.547
 19715.226667.9332298.4438289.1347412.88 53654.8
River Rch & RM=16941,83,7193.267
20860.4428293.44 34328.940763.7750477.1957320.39
River Rch & RM=16941,83,6743.956
20888.9728333.9934379.5940825.6150553.7657412.15
River Rch & RM=16941,83,6552.227
20893.4328340.3234387.5140835.2750565.7357426.49
River Rch & RM=16941,83, 6034.25
18384.9724099.0128413.3432758.0239475.0142813.16
River Rch & RM=16941,83,5078.546
28298.8538234.4446425.8951680.2375453.1452727.98
River Rch & RM=16941,83,4389.258
 28305.538249.4346448.89 51710.775497.6252765.78
River Rch & RM=16941,83, 3568.89
28400.7138463.72 46777.352145.7976132.8653305.49
Boundary for River Rch & Prof#=16941,83,1
Up Type= 0
Dn Type= 2
Boundary for River Rch & Prof#=16941,83,2
Up Type= 0
Dn Type= 2
Boundary for River Rch & Prof#=16941,83,2
Up Type= 0
Dn Type= 2
Boundary for River Rch & Prof#=16941,83,2
Up Type= 0
Dn Type= 2
Boundary for River Rch & Prof#=16941,83,2
Up Type= 0
Dn Type= 2
Boundary for River Rch & Prof#=16941,83,2
Up Type= 0
Dn Type= 2

--- 16941_ras.g01 (geometry) ---

Geom Title=16941
Program Version=4.10

River Reach=16941,83
Reach XY= 30
859561.749798732837199.264806665859013.147427588838525.784081709
859093.978017137839084.091726807 860667.73674539 841520.92153443
861055.655081989841731.527025156862797.359628305 841615.52586244
863415.616656162842580.801596591863053.960574686  843106.7933834
 864070.20789126844875.196606028 863135.72581605845650.370516979
862994.266929214846384.269866011863559.732398958847287.730390123
 864458.52268283847281.700678014864740.142119513847569.783700096
864309.117047798848233.042799363 864465.14788524848827.847583531
863765.341549571848830.741408009864158.602134489849838.680447202
864712.235954235850283.430934208864314.267362318851416.873885008
865334.035253579851813.828502789865579.252149145 852251.55829863
866358.934935313852085.611327522866509.724372864852732.858220536
867494.791370164852849.634515619867465.471962923 854915.17551527
868333.785197957855994.047678689868360.497700903856608.247513009
869975.042304244857833.284755334869816.964722392858637.641131335

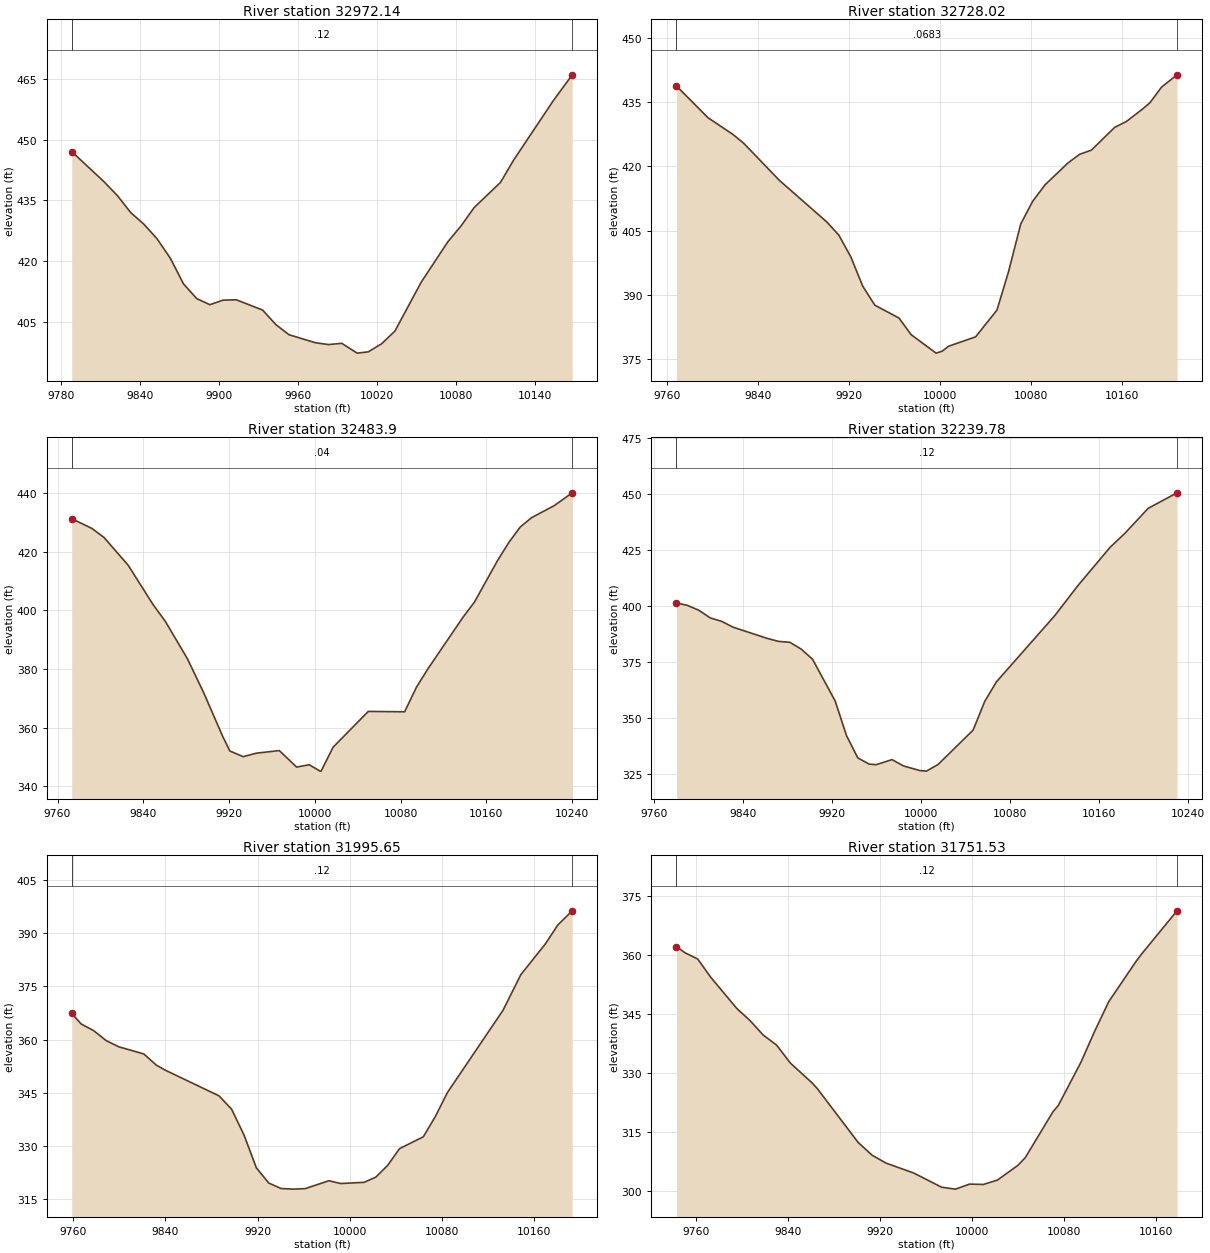
Type RM Length L Ch R = 1 ,32972.14,244.121300,244.121300,244.121300
XS GIS Cut Line= 6
859350.500701232837192.943742152859459.495079504 837202.64861407
859508.752455069837203.093550756  859566.6049264837200.452609759
859641.790564307837192.230363344 859729.46174976837190.925391923
#Sta/Elev= 30
 9788.37447.08759813.039439.58079823.108436.16649833.177 431.9799843.213429.0958
9853.235425.47349863.258420.6883 9873.28414.32099883.302410.68059893.325409.1696
9903.335410.29459913.336410.38849933.336  407.859943.337404.26219953.352401.7387
  9973.4399.76129983.424399.29859993.448399.613710005.11397.180610013.59397.4963
10023.69399.494610033.79402.630410053.91414.815510073.97424.730910083.99428.6539
10093.99433.221310113.99439.4503   10124444.9857   10154459.638310168.46466.0811
#Mann= 3 , 0 , 0
 9788.37    0.12       0 9788.37    0.12       010168.46    0.12       0
#XS Ineff= 2 , 0
       0                               0
Bank Sta=9788.37,10168.46
Exp/Cntr=0.3,0.1

Type RM Length L Ch R = 1 ,32728.02,244.121300,244.121300,244.121300
XS GIS Cut Line= 6
859318.513570351837360.203067539 859470.38550446837407.574843599
859511.885922801837422.514889469859567.043079327837446.402373374
859625.423934404837464.454209129859738.201066771837492.270909526
#Sta/Elev= 30
9768.128438.76489795.873  431.359817.821427.45699827.299425.39449858.724416.7308
9900.625406.9903  9911.1403.92849921.575398.88639932.121392.01749942.749387.6012
9964.006384.59649974.732380.7122 9996.62 376.413   10002376.851510007.53378.0086
10031.44380.211710050.23386.456110060.54395.531510071.17406.559610081.63411.8296
10092.54415.684410112.71420.783510123.01422.810910133.31423.781710153.91429.1151
10164.21430.473110178.15433.334910184.82434.825210195.12438.4933 10208.7441.3601
#Mann= 3 , 0 , 0
9768.128  0.0683       09768.128  0.0683       0 10208.7  0.0683       0
#XS Ineff= 2 , 0
       0                               0
Bank Sta=9768.128,10208.7
Exp/Cntr=0.3,0.1

Type RM Length L Ch R = 1 , 32483.9,244.121300,244.121300,244.121300
XS GIS Cut Line= 6
859257.947347426837533.053370317859308.080162356837558.318819115
859347.010982659 837581.35326733859439.280275507837647.829062785
859553.286127809837702.259467691859670.822843198837745.597256137
#Sta/Elev= 30
9773.206431.20559792.131427.87479803.384424.7873 9825.89415.33559849.016401.9806
9860.636396.15459881.089383.50689896.327371.8786 9914.06356.98849920.694352.0303
9933.156350.09839945.618351.29659966.839352.17099983.004346.54039994.718347.3429
10004.81345.167710005.81345.171610016.97353.312110049.82365.518310083.72365.3896
10094.67373.730510105.62380.136610138.01397.551410148.75402.742810170.22 416.844
10180.95423.131410191.57428.392110202.14431.560710223.28435.6756   10240440.0186
#Mann= 3 , 0 , 0
9773.206    0.04       09773.206    0.04       0   10240    0.04       0
#XS Ineff= 2 , 0
       0                               0
Bank Sta=9773.206,10240
Exp/Cntr=0.3,0.1

Type RM Length L Ch R = 1 ,32239.78,244.121300,244.121300,244.121300
XS GIS Cut Line= 6
859165.592978202837789.092291302859224.882324319837803.789015629
859335.973265951837823.706449434859379.241775358837834.396395219
859385.166958603837835.798453696859599.717964886837902.940135516
#Sta/Elev= 30
9780.484401.30649790.176400.26099800.479398.10069810.782394.65619821.084393.1136
9831.387390.50079862.007385.51429872.166384.18119882.326383.76859892.485380.7388
9902.644376.22979922.963357.61099933.123 342.1999943.282332.20769953.442329.4262
9959.824329.17859974.029331.4279 9984.33328.6083    9999326.547810004.92326.2948
10015.39329.264710046.83344.593110057.31357.448810067.78366.141110120.17395.6809
10141.13 409.19510169.83426.148710183.04432.3556   10204443.5279 10229.9450.4546
#Mann= 3 , 0 , 0
9780.484    0.12       09780.484    0.12       0 10229.9    0.12       0
#XS Ineff= 2 , 0
       0                               0
Bank Sta=9780.484,10229.9
Exp/Cntr=0.3,0.1

Type RM Length L Ch R = 1 ,31995.65,244.121300,244.121300,244.121300
XS GIS Cut Line= 6
859087.473981416837982.751825105859259.380134985838055.173298141
859284.569310094 838062.56527802859343.502816357838074.054880335
 859382.26851594838084.552004246859496.674576502838126.358127041
#Sta/Elev= 30
9758.513367.42019766.708364.43869777.597362.55759788.486 359.7439799.375358.0064
9821.153355.99249832.042352.83619839.998351.38919886.488344.18149897.377340.4428
9908.194333.17429918.921323.90989929.648319.62469940.375318.0669 9950.93317.8949
9961.352318.0339 9981.96320.25989992.156319.477410012.53319.805410022.71321.2739
10032.92324.545110043.28 329.296   10064332.647710074.42  338.3510085.01345.1567
10133.26368.314410148.76378.358610170.16 387.05510180.86392.344910193.35396.3181
#Mann= 3 , 0 , 0
9758.513    0.12       09758.513    0.12       010193.35    0.12       0
#XS Ineff= 2 , 0
       0                               0
Bank Sta=9758.513,10193.35
Exp/Cntr=0.3,0.1

Type RM Length L Ch R = 1 ,31751.53,244.121300,244.121300,244.121300
XS GIS Cut Line= 6
858958.299721185838127.132889759858979.595822713838137.491083084
859026.951175465838163.584581959859090.234848484838203.248947406
859282.431761085838334.957487303859325.851454675838360.523683025
#Sta/Elev= 30
9742.748362.20669750.199360.62949761.319359.0261  9772.6354.38489795.435346.3999
9806.853343.3373 9818.27 339.6629829.997337.08989841.993332.50649860.822327.4809
9865.403326.0096 9900.96312.29819913.079309.04869925.198307.04179949.436304.4942
9973.675300.88459985.794300.40469997.913301.683110010.03301.596410022.16302.6988
10039.86306.423410046.41308.404310070.66320.154410075.22321.727810094.92332.7361
10107.04340.734310119.17348.184410142.77358.370410147.97360.396710178.57371.3183
#Mann= 3 , 0 , 0
9742.748    0.12       09742.748    0.12       010178.57    0.12       0
#XS Ineff= 2 , 0
       0                               0
Bank Sta=9742.748,10178.57
Exp/Cntr=0.3,0.1

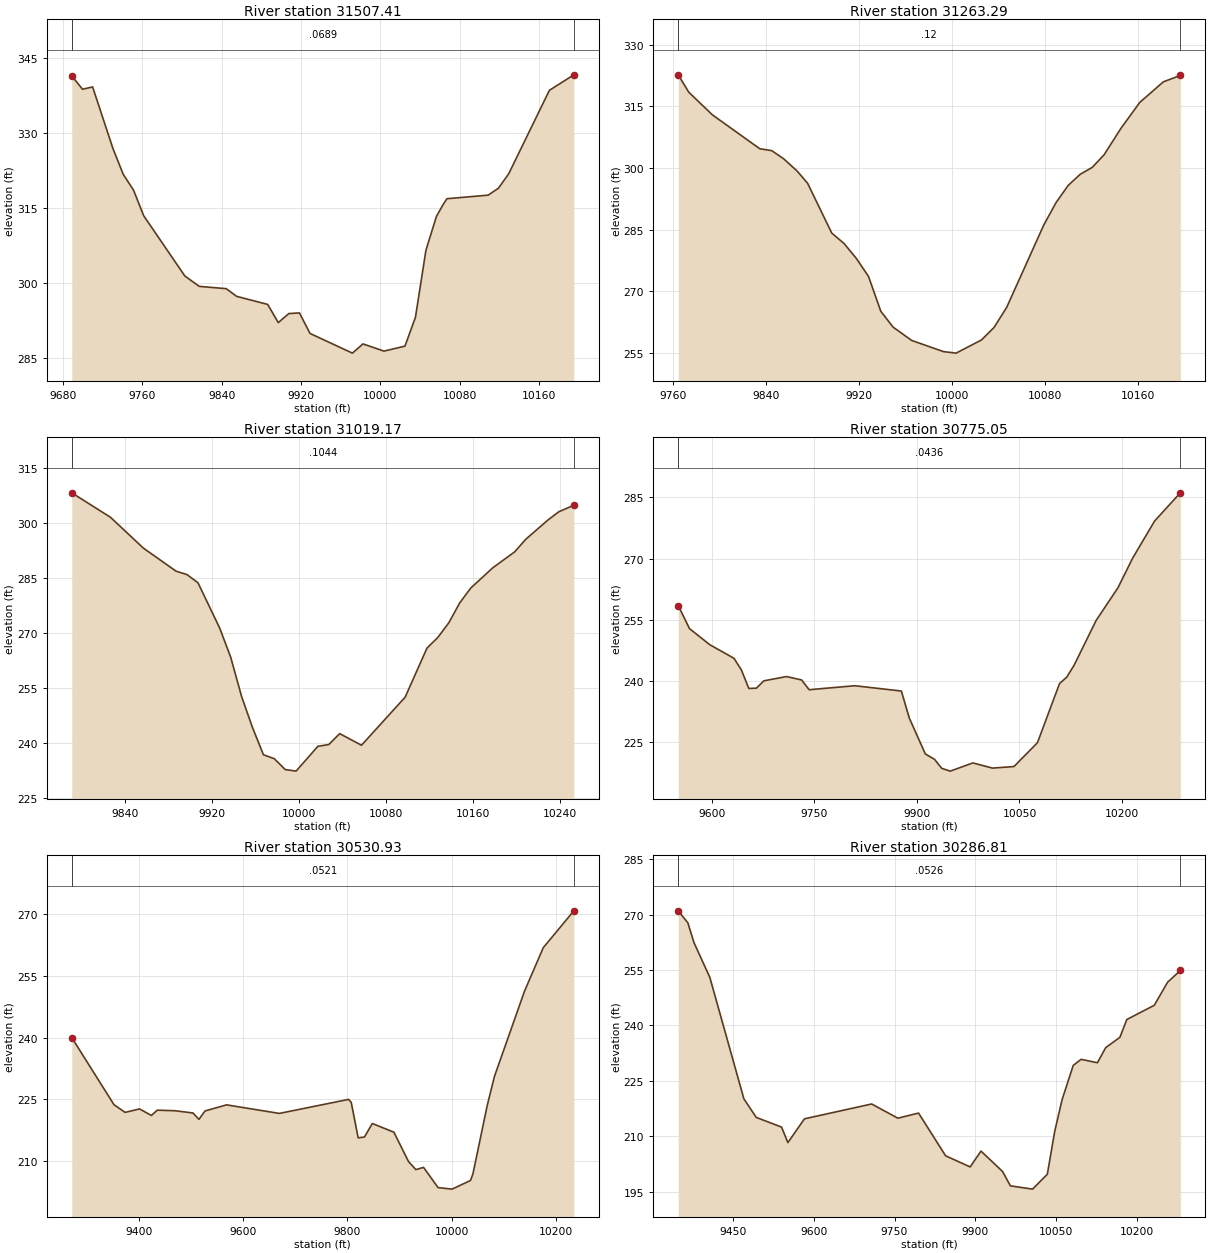
Type RM Length L Ch R = 1 ,31507.41,244.121300,244.121300,244.121300
XS GIS Cut Line= 6
858754.452911473838372.964677065858842.293223666838394.058961062
858943.392102299838424.248596564859120.080405805838487.991045918
859185.421373875838505.852400114859239.110283608838517.193295481
#Sta/Elev= 30
9688.705341.4117  9699.5338.72039709.734339.18549730.307326.81259740.614321.6881
9750.921318.55359761.228313.40639802.749301.33679817.289299.26139844.494   298.8
9854.931297.26779886.279295.64949896.958292.00759907.637293.81889918.316293.9462
9928.994289.8392 9971.71285.89949982.389287.743810003.55 286.30210024.71287.2977
10035.29293.074110045.88306.505210056.46313.263810063.27315.664110067.04 316.808
10108.61317.521810118.98318.908610129.35321.798210170.38338.507810195.03341.6076
#Mann= 3 , 0 , 0
9688.705  0.0689       09688.705  0.0689       010195.03  0.0689       0
#XS Ineff= 2 , 0
       0                               0
Bank Sta=9688.705,10195.03
Exp/Cntr=0.3,0.1

Type RM Length L Ch R = 1 ,31263.29,244.121300,244.121300,244.121300
XS GIS Cut Line= 6
858846.082396431838745.071764544858967.678624192838719.903862742
859030.103954515838699.128668397 859153.64676808838648.966129275
859204.958996209838635.645610769859259.464205988 838627.50466325
#Sta/Elev= 30
9764.422322.69089773.459318.46849793.727312.95649834.526304.68679844.804304.2281
9855.083302.23219866.625299.25959875.639296.26939896.387284.15099906.926281.6157
9917.466278.00039928.005273.58049938.544265.10899949.083261.25269965.058258.0046
9992.353255.286710003.25254.910710025.07258.113410035.98261.192610046.76266.0612
10078.66286.127210089.25291.595410099.59 295.74410109.92298.463710120.25300.1406
10130.58303.2495 10144.9309.629710161.17315.980810181.43320.9829   10196 322.545
#Mann= 3 , 0 , 0
9764.422    0.12       09764.422    0.12       0   10196    0.12       0
#XS Ineff= 2 , 0
       0                               0
Bank Sta=9764.422,10196
Exp/Cntr=0.3,0.1

Type RM Length L Ch R = 1 ,31019.17,244.121300,244.121300,244.121300
XS GIS Cut Line= 6
858899.758830447838926.476539961859062.118556853838911.611656195
859121.478421566838911.738135732859220.988699476838905.876882422
859272.925825014838900.934450901859358.474942354838886.950625666
#Sta/Elev= 30
9791.444308.14469826.964301.48339857.143293.08289887.275286.76759897.297285.8399
9907.319283.62599927.362271.20399937.384263.32119947.406252.58179957.421244.1316
9967.422236.72199977.422235.63999987.422232.68059997.422232.253110017.43239.0181
10027.45239.509810037.47242.4748 10057.5239.320610097.57252.422610117.62265.8021
10127.66268.740510137.71272.725710147.75278.1555 10157.8282.173310177.96287.6817
10198.16292.051610208.27295.460510228.55300.697710238.74 302.99410252.47 304.752
#Mann= 3 , 0 , 0
9791.444  0.1044       09791.444  0.1044       010252.47  0.1044       0
#XS Ineff= 2 , 0
       0                               0
Bank Sta=9791.444,10252.47
Exp/Cntr=0.3,0.1

Type RM Length L Ch R = 1 ,30775.05,244.121200,244.121200,244.121200
XS GIS Cut Line= 6
858739.804850058 839342.88386988858945.656022151839251.661518857
859025.299824631839210.266271929859113.313551523 839152.19542341
859175.808027583839097.449145513859390.107445388839013.392771701
#Sta/Elev= 30
9551.004258.51339567.478252.86289597.294248.90619632.529245.59019643.371 242.734
9654.218238.19919665.242238.27599676.265240.07419709.337 241.1189731.384240.2885
9742.408237.89619809.273238.87129877.281 237.5739888.952230.92289912.292222.1692
9925.762220.84859936.288218.64059948.733217.95379981.877219.962110010.59218.6962
10041.94 219.076 10076.3224.922610108.54239.390910119.24241.001710129.94243.9148
10162.03254.845510194.13262.908410215.52270.138110247.62279.227710285.18286.1269
#Mann= 3 , 0 , 0
9551.004  0.0436       09551.004  0.0436       010285.18  0.0436       0
#XS Ineff= 2 , 0
       0                               0
Bank Sta=9551.004,10285.18
Exp/Cntr=0.3,0.1

Type RM Length L Ch R = 1 ,30530.93,244.121300,244.121300,244.121300
XS GIS Cut Line= 6
858698.793909158839730.233899964858890.956540139839631.590581009
859106.103563517839491.238526024859246.845247617839364.778414225
859356.232394734839244.698511153859461.094168788 839155.22849813
#Sta/Elev= 30
9271.601239.9907 9352.62223.66719373.916221.80019401.622222.64179424.275221.0532
9435.602222.34079469.581 222.2039503.949221.65749515.553220.10689527.156222.1494
9568.533223.63099669.671221.54999802.488224.95869807.605224.22239820.912 215.605
9832.905215.80959848.063219.09329889.435216.98239917.486 209.8369931.512 207.883
  9946.3208.42169974.135203.5053   10001203.131510036.42205.243110041.04206.8528
10068.51 223.53910082.32 230.569   10140251.309410175.95261.879310234.54270.8361
#Mann= 3 , 0 , 0
9271.601  0.0521       09271.601  0.0521       010234.54  0.0521       0
#XS Ineff= 2 , 0
       09877.076                       0
Bank Sta=9271.601,10234.54
Exp/Cntr=0.3,0.1

Type RM Length L Ch R = 1 ,30286.81,244.121300,244.121300,244.121300
XS GIS Cut Line= 6
858939.282045728839853.383768922859173.177663087839715.342378054
 859283.82184161839639.414253093859422.624209169839526.475467079
859596.743313168 839366.45172415859683.962412057839299.811120422
#Sta/Elev= 30
9348.877271.00759366.733267.76079378.098 262.3949407.457253.01129470.646220.1195
9493.586215.09739540.524 212.4759552.258208.28569582.957214.71599707.634218.7321
9756.208214.88839794.579216.26939844.762204.71029890.292201.69499910.366205.9849
9950.383200.46869964.891196.578410006.01 195.68910033.44199.709910047.16 211.358
10060.88219.9338 10081.5229.174310096.11230.815310126.35229.894110141.74233.9939
10167.98236.761210180.82241.586610231.74245.440410256.54251.695110280.06254.8632
#Mann= 3 , 0 , 0
9348.877  0.0526       09348.877  0.0526       010280.06  0.0526       0
#XS Ineff= 2 , 0
       09853.903                       0
Bank Sta=9348.877,10280.06
Exp/Cntr=0.3,0.1

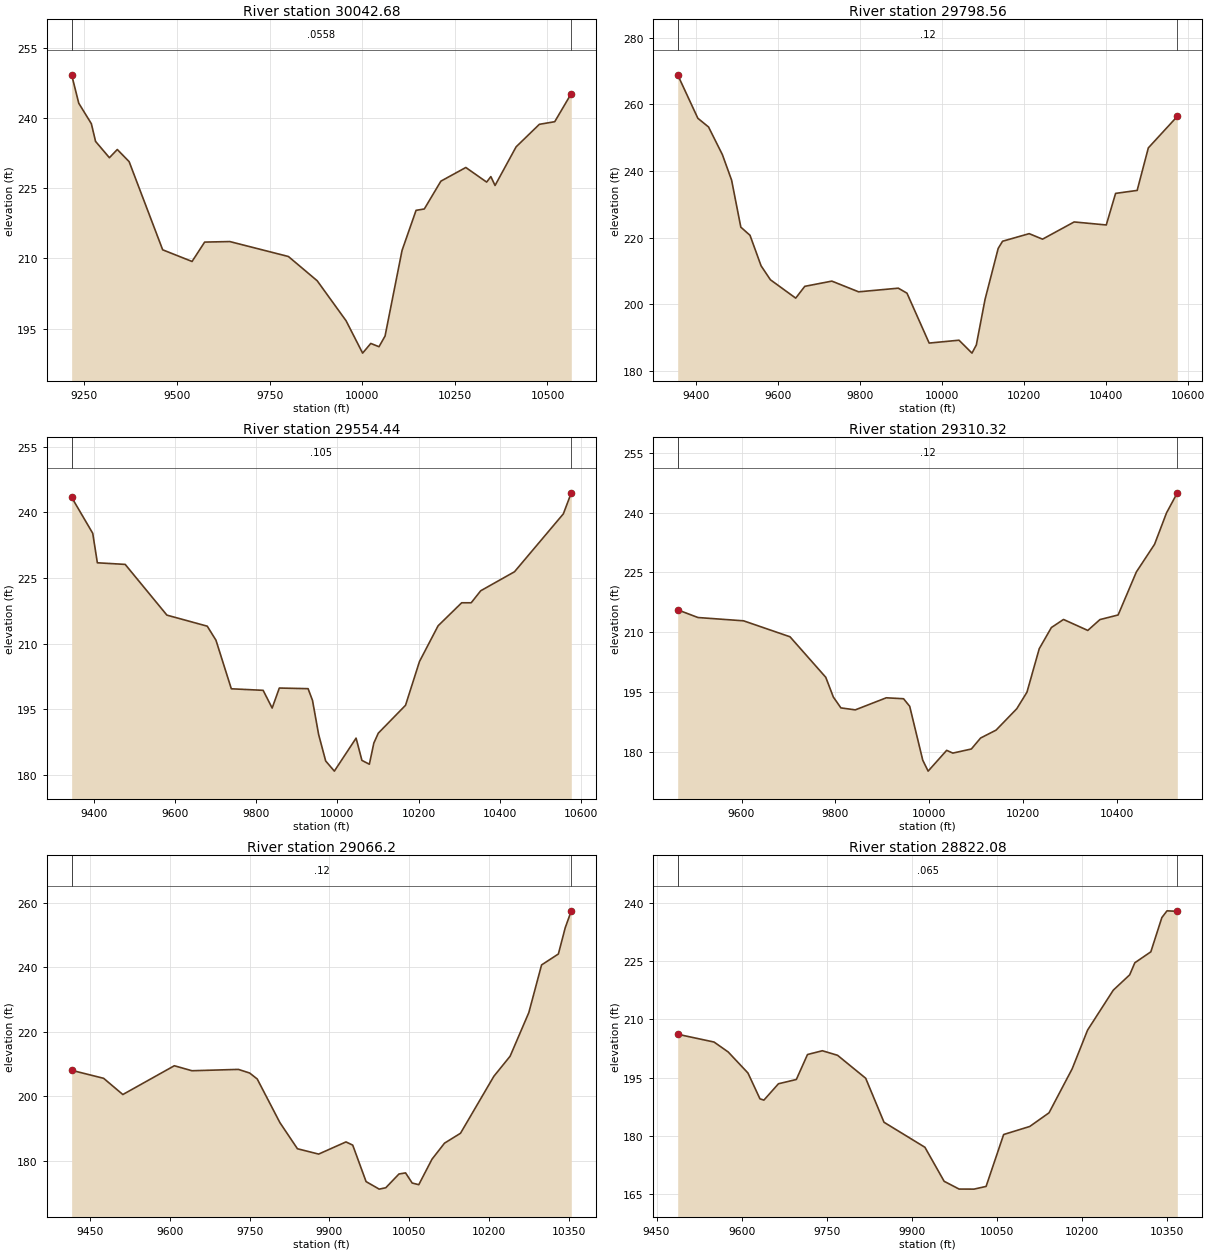
Type RM Length L Ch R = 1 ,30042.68,244.121300,244.121300,244.121300
XS GIS Cut Line= 6
858908.019033306840042.848600102859403.781589338 839779.24821642
859772.724929482839600.196510646859900.716697223839534.926786526
860035.425833744839462.166129028860105.742144644839423.410383938
#Sta/Elev= 30
9215.624249.19229234.856243.12559268.833238.75179280.159234.97829317.544231.4915
9338.845233.24459370.764230.6571 9461.37211.8218 9540.65209.33719574.627213.4745
9642.581213.58559800.697210.39599878.397205.21729956.334196.6775   10001189.7632
10023.04191.832210045.26191.130910061.57193.409510107.42211.691910145.28220.2533
10167.51220.545310212.21226.482210279.56 229.40410335.75226.287810347.11227.4654
10358.48225.566210415.31233.814110478.02238.622110519.54239.183610564.27245.1987
#Mann= 3 , 0 , 0
9215.624  0.0558       09215.624  0.0558       010564.27  0.0558       0
#XS Ineff= 2 , 0
       09820.001                       0
Bank Sta=9215.624,10564.27
Exp/Cntr=0.3,0.1

Type RM Length L Ch R = 1 ,29798.56,244.121300,244.121300,244.121300
XS GIS Cut Line= 6
859087.972997006840177.417111899859347.532189766840046.568267221
859501.065404218 839978.17743804 859908.67978653839826.859883364
860044.850151721839760.924139768860196.283566427839676.294144655
#Sta/Elev= 30
9355.112268.89079404.271255.86139430.426253.23379464.135244.94779486.607237.2897
 9509.08223.19339531.553 220.7319558.512211.58599581.224207.40649642.978201.8926
9665.043205.42929731.134206.99789796.413203.78319893.159204.87939914.323203.3774
9968.406188.407910041.18189.266810072.83185.391710083.41187.834210104.75201.5427
10136.76216.811410147.43218.961810212.34221.239210244.86219.580310322.02224.7486
10400.33223.845310423.07233.318910475.66234.210310502.93246.971310573.65256.4394
#Mann= 3 , 0 , 0
9355.112    0.12       09355.112    0.12       010573.65    0.12       0
#XS Ineff= 2 , 0
       09876.856                       0
Bank Sta=9355.112,10573.65
Exp/Cntr=0.3,0.1

Type RM Length L Ch R = 1 ,29554.44,244.121300,244.121300,244.121300
XS GIS Cut Line= 6
859189.535783376  840434.5010516859559.689027231840234.341702937
859684.121026694840174.025092317859927.353195817840069.168724177
860094.607284514839971.752339142860271.205770395839855.056232224
#Sta/Elev= 30
9346.066243.42569397.937235.20429409.346228.46029477.801228.08949580.483216.4921
9679.769213.96549701.196210.7554 9738.97199.65199817.239199.29839839.465195.2436
9857.079199.82259927.852199.67919938.718197.00339953.807 189.2029971.141183.1503
 9992.46180.826910045.98188.368110060.32183.285510078.61182.401310089.61187.2364
10100.61189.504410167.63195.879510201.96205.888810247.81214.057310305.79 219.315
 10329.2219.316310352.61  222.0610435.75226.405710555.94239.642410575.54244.4532
#Mann= 3 , 0 , 0
9346.066   0.105       09346.066   0.105       010575.54   0.105       0
#XS Ineff= 2 , 0
       09894.692                       0
Bank Sta=9346.066,10575.54
Exp/Cntr=0.3,0.1

Type RM Length L Ch R = 1 ,29310.32,244.121300,244.121300,244.121300
XS GIS Cut Line= 6
859469.229026586840668.416577489859576.523313802840595.316981646
859697.025516418840507.692163574859831.094660834840401.628286884
860069.008386416840198.896390789860302.998526533840008.160806781
#Sta/Elev= 30
9463.972215.62049507.227213.68779604.283212.86069703.198208.8516 9779.37198.6793
9795.487 193.7269811.605 190.995 9842.22190.49239908.311193.52819945.047193.2914
9958.141191.39349985.976177.85119997.422175.109210036.89180.328110050.04179.6368
 10089.5180.669610109.18183.425610142.12185.407510186.14190.769410207.89194.9335
10234.07205.856310259.92211.171510285.78213.201110337.48 210.44710363.34 213.169
10402.12 214.331 10440.9225.127110479.68232.075510505.25239.988810528.21245.0072
#Mann= 3 , 0 , 0
9463.972    0.12       09463.972    0.12       010528.21    0.12       0
#XS Ineff= 2 , 0
       0                               0
Bank Sta=9463.972,10528.21
Exp/Cntr=0.3,0.1

Type RM Length L Ch R = 1 , 29066.2,244.121300,244.121300,244.121300
XS GIS Cut Line= 6
859656.111922756840912.020679873859810.695176083840794.324851736
859959.890137582840654.637242013860012.781723857840594.291413246
860190.436607244840361.019501333860303.606418597840236.900024519
#Sta/Elev= 30
9414.841208.08839475.028205.60979511.193200.58849608.087209.49819641.233207.9522
9728.713208.36839749.872 207.2419764.086205.40719806.728191.91379839.791183.8087
9879.684 182.1569931.152185.92299943.862 184.9259968.978173.64179993.683171.3113
10006.03171.734610030.88175.9944 10043.3176.334910055.72173.198910068.14172.6797
10092.98180.561610116.62185.540910146.68188.603210209.47206.237510240.05212.4484
10275.28 225.95510299.23 240.69810330.88244.088110343.83252.234510355.21257.4459
#Mann= 3 , 0 , 0
9414.841    0.12       09414.841    0.12       010355.21    0.12       0
#XS Ineff= 2 , 0
       0                               0
Bank Sta=9414.841,10355.21
Exp/Cntr=0.3,0.1

Type RM Length L Ch R = 1 ,28822.08,244.121300,244.121300,244.121300
XS GIS Cut Line= 6
859893.202115867840991.324083511859993.065616584840918.209060145
860147.847459326840788.964095237860228.029705915840707.386141421
 860398.07525451840511.173327525860524.424221871840382.206440583
#Sta/Elev= 30
9487.313 206.1759551.413204.16169576.242201.60449611.085196.16989632.239189.5052
9639.166189.16499664.771193.38729696.301194.49239715.981200.94119742.183201.9162
9768.906200.74249818.475194.8147 9850.71183.45389922.783176.99519956.665168.2069
9982.981166.200810009.22166.184310030.57166.884810061.48180.284810107.49182.3663
 10141.4 185.88610182.28 197.28210209.31207.244710254.61217.560110283.48221.5161
10292.51224.624310320.77227.465310340.14 236.29910349.23238.046510367.44237.9154
#Mann= 3 , 0 , 0
9487.313   0.065       09487.313   0.065       010367.44   0.065       0
#XS Ineff= 2 , 0
       09883.999                       0
Bank Sta=9487.313,10367.44
Exp/Cntr=0.3,0.1

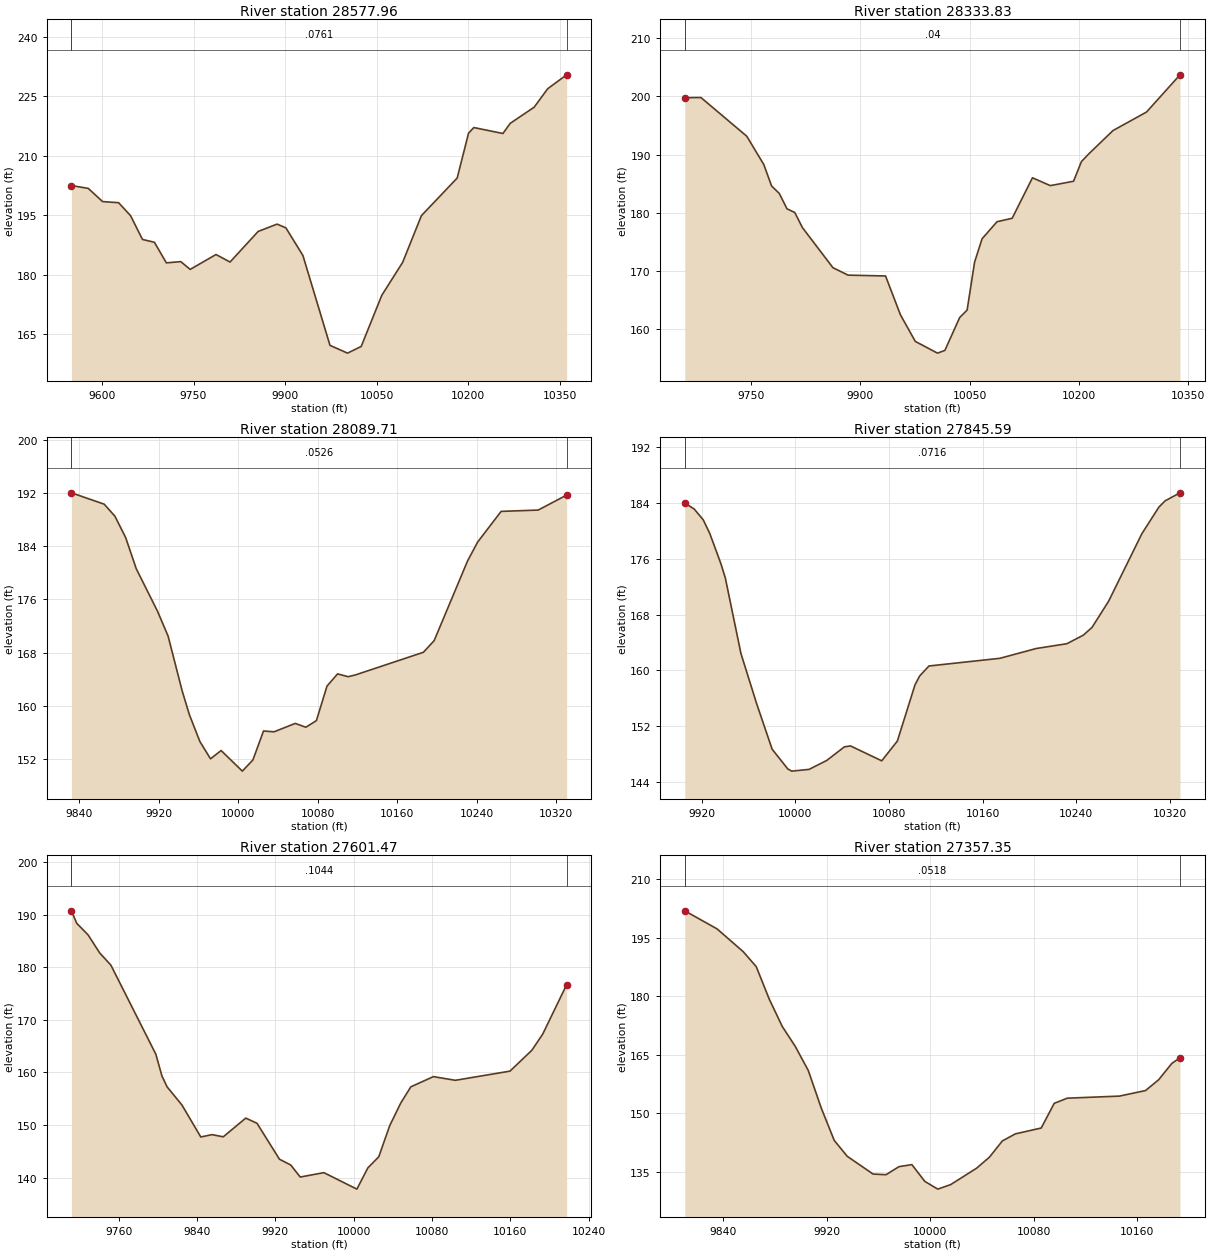
Type RM Length L Ch R = 1 ,28577.96,244.121300,244.121300,244.121300
XS GIS Cut Line= 6
860031.553578292841065.431022835860204.229837253840961.498221526
860297.798400864 840908.12643087 860516.48057769840794.050803882
860657.915549428840705.944347498860730.112334785 840653.86460988
#Sta/Elev= 30
9549.828 202.4599577.395201.73939600.909198.41139627.193198.12859646.749194.8633
9666.304188.8651 9685.86188.15529705.416182.9637    9729183.27519744.528181.3148
  9786.8185.06829809.825183.16879855.875 190.8869886.897192.72959901.299191.7932
9929.255184.81889973.593162.168410002.38160.206510024.75161.886310058.53 174.784
 10092.7183.086810123.46194.863110182.09204.352410200.71 215.65110209.36217.0773
10257.04215.579210268.97218.133110308.24222.2061 10330.5226.870610361.46230.3692
#Mann= 3 , 0 , 0
9549.828  0.0761       09549.828  0.0761       010361.46  0.0761       0
#XS Ineff= 2 , 0
       0                               0
Bank Sta=9549.828,10361.46
Exp/Cntr=0.3,0.1

Type RM Length L Ch R = 1 ,28333.83,244.121200,244.121200,244.121200
XS GIS Cut Line= 6
860194.846395488841168.288908578860287.314699403841129.254996496
860394.643340315841093.679877943860656.291659601841033.702325163
860756.844754997840994.615862601860836.206992868840952.376759065
#Sta/Elev= 30
9658.769199.7971 9680.98199.81619743.907193.16429767.319188.29059777.933184.6255
9788.547183.33469799.162180.68679809.776180.06159820.324177.46349862.171170.5803
9882.957169.29399934.455169.15049954.902162.47739975.318157.905410005.75155.8908
10015.91156.355310036.23162.003510046.48163.295910056.74171.5426   10067175.5416
10087.52178.473510108.33179.0688 10136.2186.025910160.71184.679410192.61185.4309
10203.45188.819310214.29190.228510246.82194.146110292.85197.328610338.77203.7211
#Mann= 3 , 0 , 0
9658.769    0.04       09658.769    0.04       010338.77    0.04       0
#XS Ineff= 2 , 0
       0                               0
Bank Sta=9658.769,10338.77
Exp/Cntr=0.3,0.1

Type RM Length L Ch R = 1 ,28089.71,244.121300,244.121300,244.121300
XS GIS Cut Line= 6
860404.476436263841365.369885269860456.360068921 841344.33089487
860681.548350069841261.453578396860753.027736301 841231.16437167
860813.125102451841199.807562948860861.320532017841169.907123537
#Sta/Elev= 30
9832.234192.06589865.172190.35999875.963188.55189886.754185.3399 9897.44180.6349
9918.779174.24389929.449 170.4949943.658162.21059950.789158.68429961.458154.5977
9972.128     1529982.798153.247610004.15150.143910014.79151.832410025.43156.1899
10036.07156.067210057.36157.3319   10068156.756210078.64157.749510089.28162.9452
10099.93164.792810110.57164.367110117.81 164.63110186.23168.044510197.09169.8018
10230.59181.776610240.75184.635210264.43189.269610301.68189.468910330.31191.7215
#Mann= 3 , 0 , 0
9832.234  0.0526       09832.234  0.0526       010330.31  0.0526       0
#XS Ineff= 2 , 0
       0                               0
Bank Sta=9832.234,10330.31
Exp/Cntr=0.3,0.1

Type RM Length L Ch R = 1 ,27845.59,244.121300,244.121300,244.121300
XS GIS Cut Line= 6
 860598.99359835841585.428973449860669.203263262841523.558380767
860749.208775447841452.383509555860821.398343796 841383.58877752
860888.351204323841316.102408161 860907.25961227841295.729124584
#Sta/Elev= 30
9905.419184.01189913.425183.16429921.193181.60629926.754179.66089936.319175.2886
9940.083173.24279953.411162.4038 9966.74155.24239980.069148.65449993.398145.8253
 9996.82145.498810011.65145.748710026.73 147.03110041.82148.982610047.04149.1209
10073.76146.980810087.12149.822510102.15157.8785 10106.1159.1519 10114.1160.6036
10174.78161.709210205.82163.1167   10232163.804910246.09165.038710253.53 166.156
10267.73169.926310296.12179.617710310.65183.431810316.03184.342110328.68185.4855
#Mann= 3 , 0 , 0
9905.419  0.0716       09905.419  0.0716       010328.68  0.0716       0
#XS Ineff= 2 , 0
       0                               0
Bank Sta=9905.419,10328.68
Exp/Cntr=0.3,0.1

Type RM Length L Ch R = 1 ,27601.47,244.121300,244.121300,244.121300
XS GIS Cut Line= 6
860738.830686376841889.624153598860753.442484497841865.624988475
860854.234175588841686.506922055860878.545399871841638.827358592
860879.504303628841637.072222231860975.683787255841443.167238818
#Sta/Elev= 30
9711.854190.72129717.267188.35659728.975186.12139740.668182.73499752.143180.4001
9798.041163.47419804.301159.32699809.515157.27679824.693153.82079843.939147.7416
9855.413148.18999866.888147.77229889.837151.32999901.311150.3491 9924.26143.5165
9935.735142.4232 9945.48140.13059969.621140.965810003.31137.833210014.48141.8626
10025.64143.9768 10036.8149.879210047.96154.148110058.38157.275110081.45159.2139
10103.78158.512510159.59160.254810181.91164.211410193.08167.302710217.45176.6753
#Mann= 3 , 0 , 0
9711.854  0.1044       09711.854  0.1044       010217.45  0.1044       0
#XS Ineff= 2 , 0
       09893.642                       0
Bank Sta=9711.854,10217.45
Exp/Cntr=0.3,0.1

Type RM Length L Ch R = 1 ,27357.35,488.242600,488.242600,488.242600
XS GIS Cut Line= 6
861075.417891416841919.702318174861085.570763708841851.059110638
861091.094103446841780.289305832861091.218144884841689.372676796
 861093.63866013841643.098501281861108.428080918841538.738025964
#Sta/Elev= 30
 9810.23201.85559835.201197.22759855.419191.39579865.528187.54289875.636179.1785
9885.698172.19389895.728167.10219905.759160.94999915.789151.32889925.819 143.042
 9935.85138.96769955.895134.40619965.895134.24139975.895136.30139985.895136.8259
9995.896132.5355 10005.9130.5451 10015.9131.7048 10035.9135.8914 10045.9 138.734
10055.92142.901510065.93144.700510085.96146.205210096.02  152.53 10106.1153.8502
10146.39154.378610166.63155.800510176.79158.565110186.94  162.74 10193.3 164.213
#Mann= 3 , 0 , 0
 9810.23  0.0518       0 9810.23  0.0518       0 10193.3  0.0518       0
#XS Ineff= 2 , 0
       0                               0
Bank Sta=9810.23,10193.3
Exp/Cntr=0.3,0.1

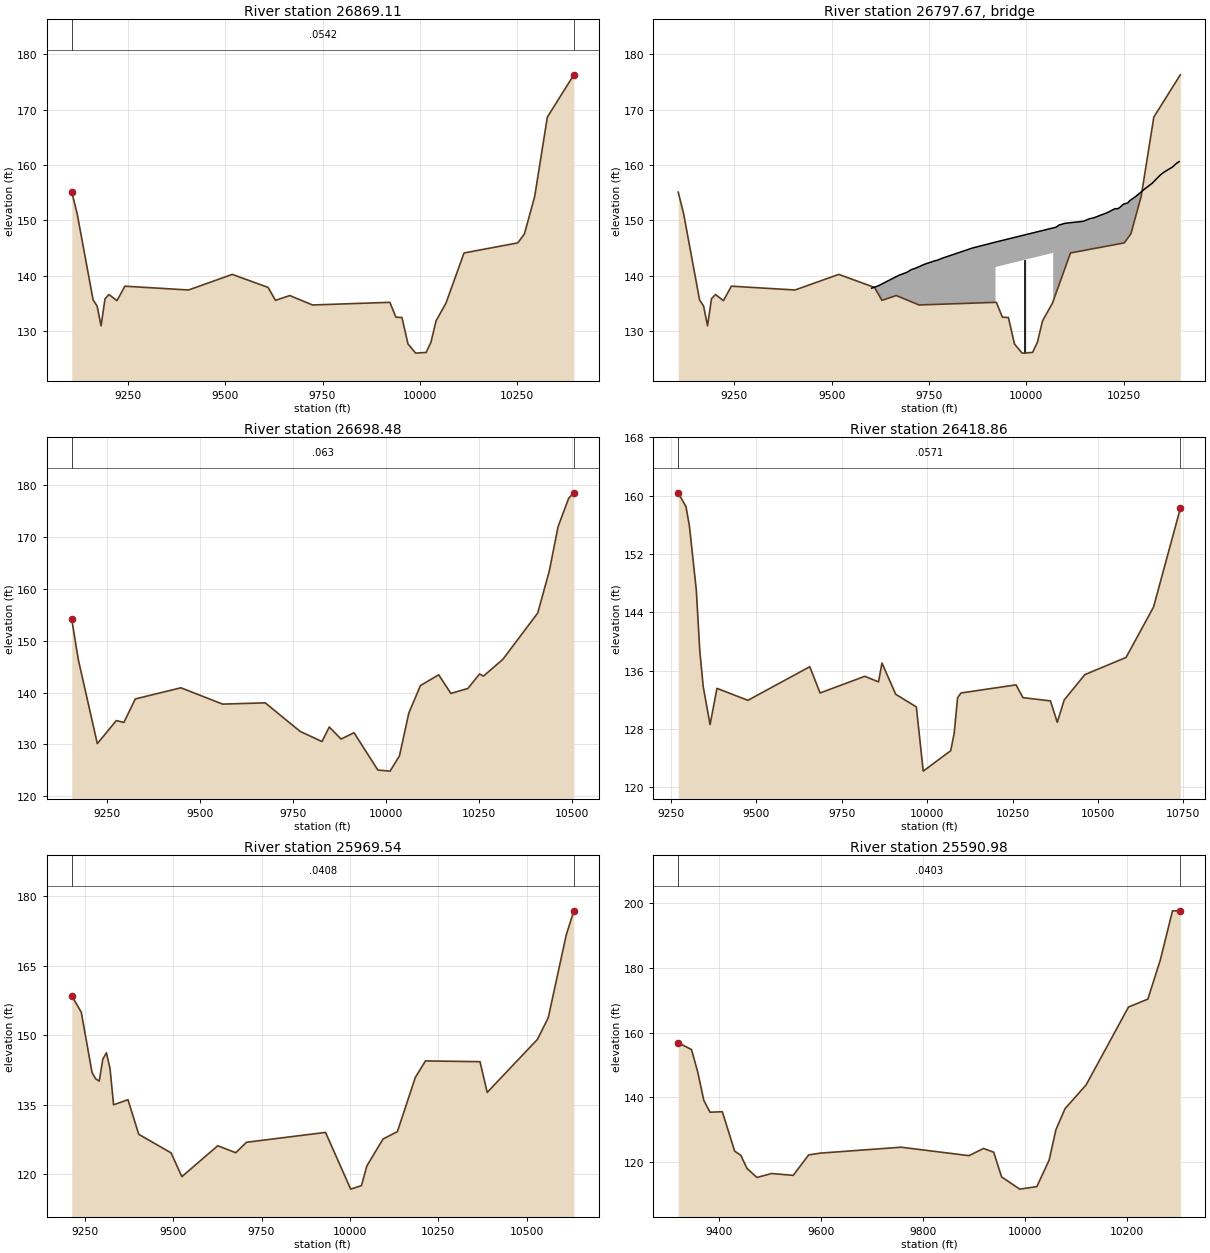
Type RM Length L Ch R = 1 ,26869.11,170.623600,170.623600,170.623600
XS GIS Cut Line= 6
861938.652228447842458.674296406861834.200541984841946.322651231
861780.912060081841858.081277325861528.156007042841644.259246324
861351.188276114841569.954824404861222.233335933841516.259769065
#Sta/Elev= 30
9106.328155.09429120.283151.15779161.106135.62219171.312134.53099181.517130.9503
9191.723135.83379201.929136.5945 9222.34135.49269242.751138.10549406.043137.4163
9518.305140.23419610.156137.88229629.218135.53949665.809136.41339724.394134.7093
9922.827135.18969938.316132.50629953.804132.44779969.292127.6807 9988.93126.0125
10015.76126.137910028.22127.968110041.31131.831610066.79135.040110113.12144.1041
10251.17145.925510268.19147.5589 10294.5154.3083   10327168.650710394.99176.2831
#Mann= 3 , 0 , 0
9106.328  0.0542       09106.328  0.0542       010394.99  0.0542       0
#XS Ineff= 2 , 0
       09908.941        10082.98       0
Bank Sta=9106.328,10394.99
Exp/Cntr=0.3,0.1

Type RM Length L Ch R = 3 ,26797.67,,,
BEGIN DESCRIPTION:
END DESCRIPTION:
Bridge Culvert--1,0,-1,-1, 0
Deck Dist Width WeirC Skew NumUp NumDn MinLoCord MaxHiCord MaxSubmerge Is_Ogee
68.311800,34.000000,2.6,0, 36, 36, , , 0.95, 0, 0,0,,
 9602.65 9619.48 9672.60 9693.84 9704.46 9715.08 9737.43 9766.92 9769.80 9783.70
 9861.03 9920.63 9920.6310068.6310068.6310076.2010083.2410098.4110146.3210162.37
10172.3410207.5810227.8410233.1510238.6910249.1610259.6210265.3510280.5610301.49
10322.4210343.3610353.8210374.7610385.2210391.95
  137.74  138.16  140.07  140.63  141.10  141.34  142.04  142.74  142.75  143.15
  144.99  146.07  146.07  148.63  148.63  148.76  149.13  149.46  149.83  150.30
  150.44  151.39  152.12  152.08  152.27  152.93  153.12  153.56  154.31  155.55
  156.68  158.17  158.73  159.62  160.29  160.60
 -862.26 -861.84 -859.93 -859.37 -858.90 -858.66 -857.96 -857.26 -857.25 -856.85
 -855.01 -853.93  141.57  144.13 -851.37 -851.24 -850.87 -850.54 -850.17 -849.70
 -849.56 -848.61 -847.88 -847.92 -847.73 -847.07 -846.88 -846.44 -845.69 -844.45
 -843.32 -841.83 -841.27 -840.38 -839.71 -839.40
 9602.65 9619.48 9672.60 9693.84 9704.46 9715.08 9737.43 9766.92 9769.80 9783.70
 9861.03 9919.50 9919.5010067.5010067.5010076.2010083.2410098.4110146.3210162.37
10172.3410207.5810227.8410233.1510238.6910249.1610259.6210265.3510280.5610301.49
10322.4210343.3610353.8210374.7610385.2210391.95
  137.74  138.16  140.07  140.63  141.10  141.34  142.04  142.74  142.75  143.15
  144.99  146.05  146.05  148.61  148.61  148.76  149.13  149.46  149.83  150.30
  150.44  151.39  152.12  152.08  152.27  152.93  153.12  153.56  154.31  155.55
  156.68  158.17  158.73  159.62  160.29  160.60
 -862.26 -861.84 -859.93 -859.37 -858.90 -858.66 -857.96 -857.26 -857.25 -856.85
 -855.01 -853.95  141.55  144.11 -851.39 -851.24 -850.87 -850.54 -850.17 -849.70
 -849.56 -848.61 -847.88 -847.92 -847.73 -847.07 -846.88 -846.44 -845.69 -844.45
 -843.32 -841.83 -841.27 -840.38 -839.71 -839.40
Pier Skew, UpSta & Num, DnSta & Num=  ,9994.63, 2 ,9993.50, 2 , 0 , 0 , 0 ,,
    4.00    4.00
 -852.65  147.35
    4.00    4.00
 -852.67  147.33
BR Coef=-1 , 0 , 0 ,, 0 ,,,0.8,0,1,0,
WSPro=,,,, 1 ,,,, 0 ,,,, 0 ,,,,-1 ,-1 ,-1 , 0 , 0 , 0 , 0 , 0
BC Design=,, 0 ,, 0 ,,,,,,

Type RM Length L Ch R = 1 ,26698.48,279.624000,279.624000,279.624000
XS GIS Cut Line= 6
  862017.0378476842432.303124468861933.963632457842042.007379404
861859.444306015841786.651611274861809.471819287841702.350726763
861588.275908564841531.807008209861291.842889271 841442.77939258
#Sta/Elev= 30
9154.116 154.0739171.807146.31689222.927130.15769274.047134.59589294.495 134.242
9325.167138.76119447.855140.90969560.454137.76569675.043138.01229768.797132.5197
9827.877130.55989847.488133.36599879.207131.03869914.081 132.2579978.332125.0701
10011.09124.863110036.45127.798810061.71136.062810092.97141.337710142.11143.4155
10174.86139.824210220.77140.7801 10252.1143.578910262.54143.156810314.74146.3791
10408.71155.305910440.04163.4471 10463.5171.928310492.24177.429910505.98178.4493
#Mann= 3 , 0 , 0
9154.116   0.063       09154.116   0.063       010505.98   0.063       0
#XS Ineff= 2 , 0
       09903.571        10085.57       0
Bank Sta=9154.116,10505.98
Exp/Cntr=0.3,0.1

Type RM Length L Ch R = 1 ,26418.86,449.315700,449.315700,449.315700
XS GIS Cut Line= 2
 862103.82232455842357.624197871861937.942589042840897.186140919
#Sta/Elev= 30
9271.159160.38639293.929158.47569303.993155.79599324.122147.04199334.186138.7574
 9344.25133.80949364.379128.59019384.508133.56649475.086131.92399656.244136.5333
9686.436132.93159817.272135.2174 9857.53134.45459867.594137.03789907.851132.7518
9968.237131.01789988.365 122.21110068.88125.013710078.94127.374910089.01132.2843
10099.07132.9308 10260.1134.044310280.23132.293810360.74131.843310380.87128.9031
   10401131.962510461.39 135.44510582.16137.807310662.67144.723510740.99158.2394
#Mann= 3 , 0 , 0
9271.159  0.0571       09271.159  0.0571       010740.99  0.0571       0
#XS Ineff= 2 , 0
       09834.083        10364.81       0
Bank Sta=9271.159,10740.99
Exp/Cntr=0.3,0.1

Type RM Length L Ch R = 1 ,25969.54,378.568100,378.568100,378.568100
XS GIS Cut Line= 2
862314.114165799842321.440778309862570.866353146840923.817941847
#Sta/Elev= 30
9212.953  158.489239.836154.96069270.338141.96659280.505140.58849290.672140.1028
 9300.84144.83479311.007146.21269321.174142.81719331.342134.99969372.011136.0925
9402.513128.63539494.019124.63749524.521119.50879626.195 126.1749677.031124.6651
9707.533126.92069931.215129.049110002.39116.820210032.89117.576810048.04121.8103
10093.89127.618410134.56129.2129 10185.4140.914310214.08144.456610368.41144.2883
10388.75137.667210531.09149.109710561.59153.778110612.43 171.59910633.96176.8038
#Mann= 3 , 0 , 0
9212.953  0.0408       09212.953  0.0408       010633.96  0.0408       0
#XS Ineff= 2 , 0
       09652.995        10142.63       0
Bank Sta=9212.953,10633.96
Exp/Cntr=0.3,0.1

Type RM Length L Ch R = 1 ,25590.98,376.243500,376.243500,376.243500
XS GIS Cut Line= 2
862438.152074932842196.499825233862992.203921218841382.332758051
#Sta/Elev= 30
9319.419156.86559345.425154.77289357.521147.95049369.617139.09129381.712135.4423
9405.904135.59429430.096123.43859442.192122.15999454.288118.09799473.788115.3102
9502.671 116.5369544.886115.95889575.246122.2613 9598.21122.82079756.684124.6438
9889.739122.03159918.153124.25979938.122123.11089953.702115.48369989.251111.7125
10022.79  112.4810046.98120.685310060.35130.082110078.12136.538710119.56143.8901
10202.55167.883210240.52170.331310264.71182.2267 10288.9197.568310304.22197.5666
#Mann= 3 , 0 , 0
9319.419  0.0403       09319.419  0.0403       010304.22  0.0403       0
#XS Ineff= 2 , 0
       09444.126                       0
Bank Sta=9319.419,10304.22
Exp/Cntr=0.3,0.1