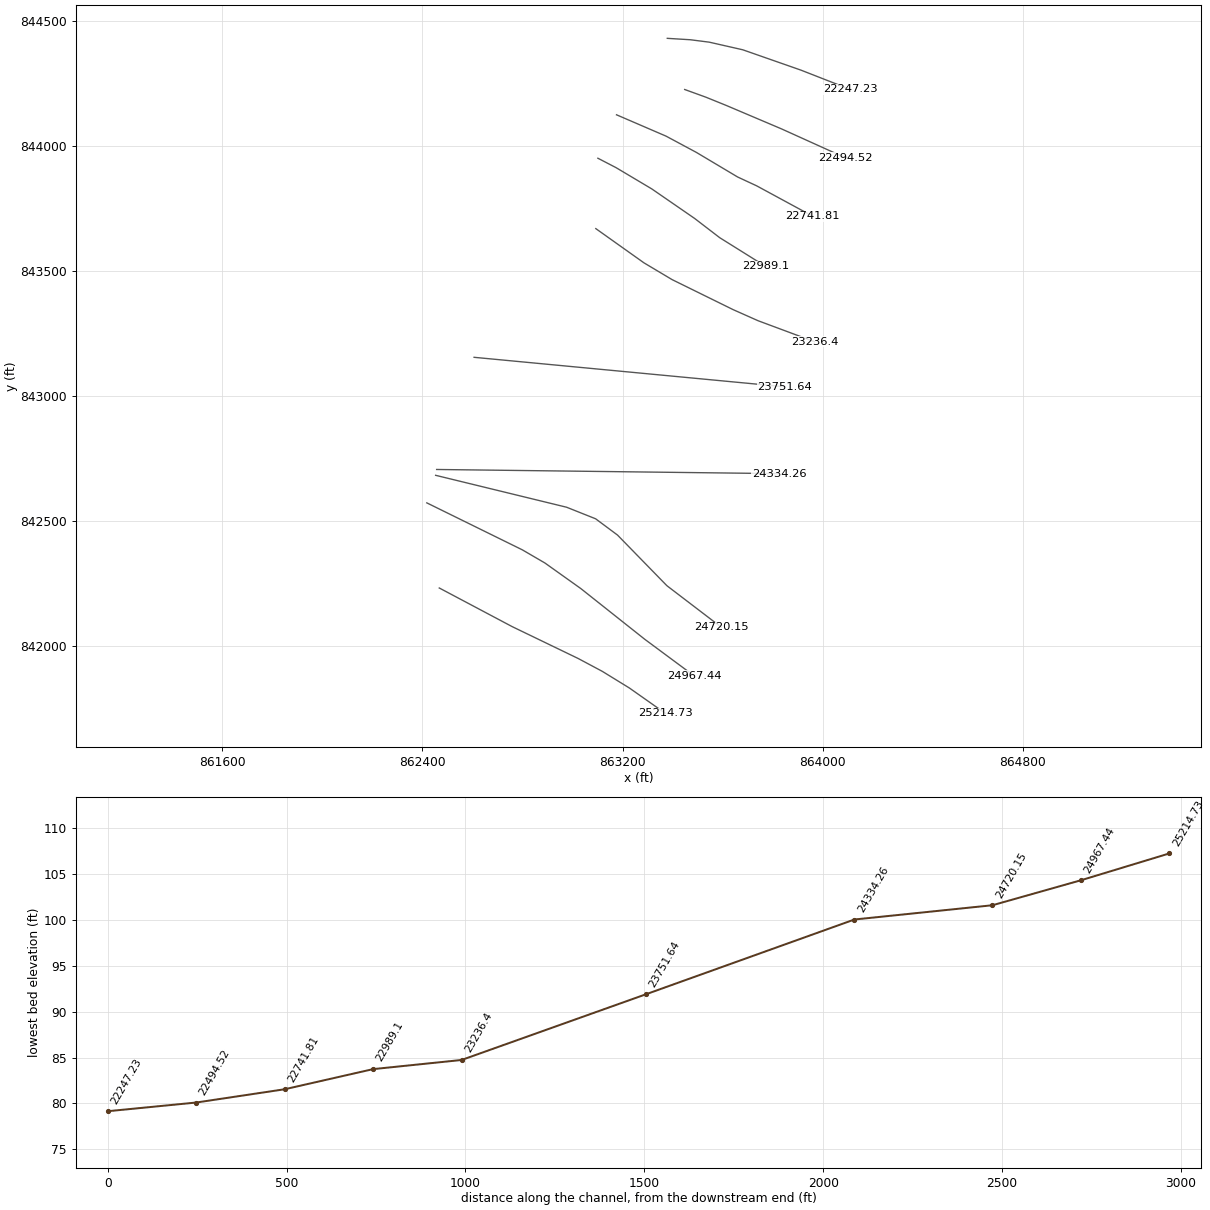
HEC-RAS study 16941_ras.prj: 16941

--- 16941_ras.g01 (geometry) --- (continued)

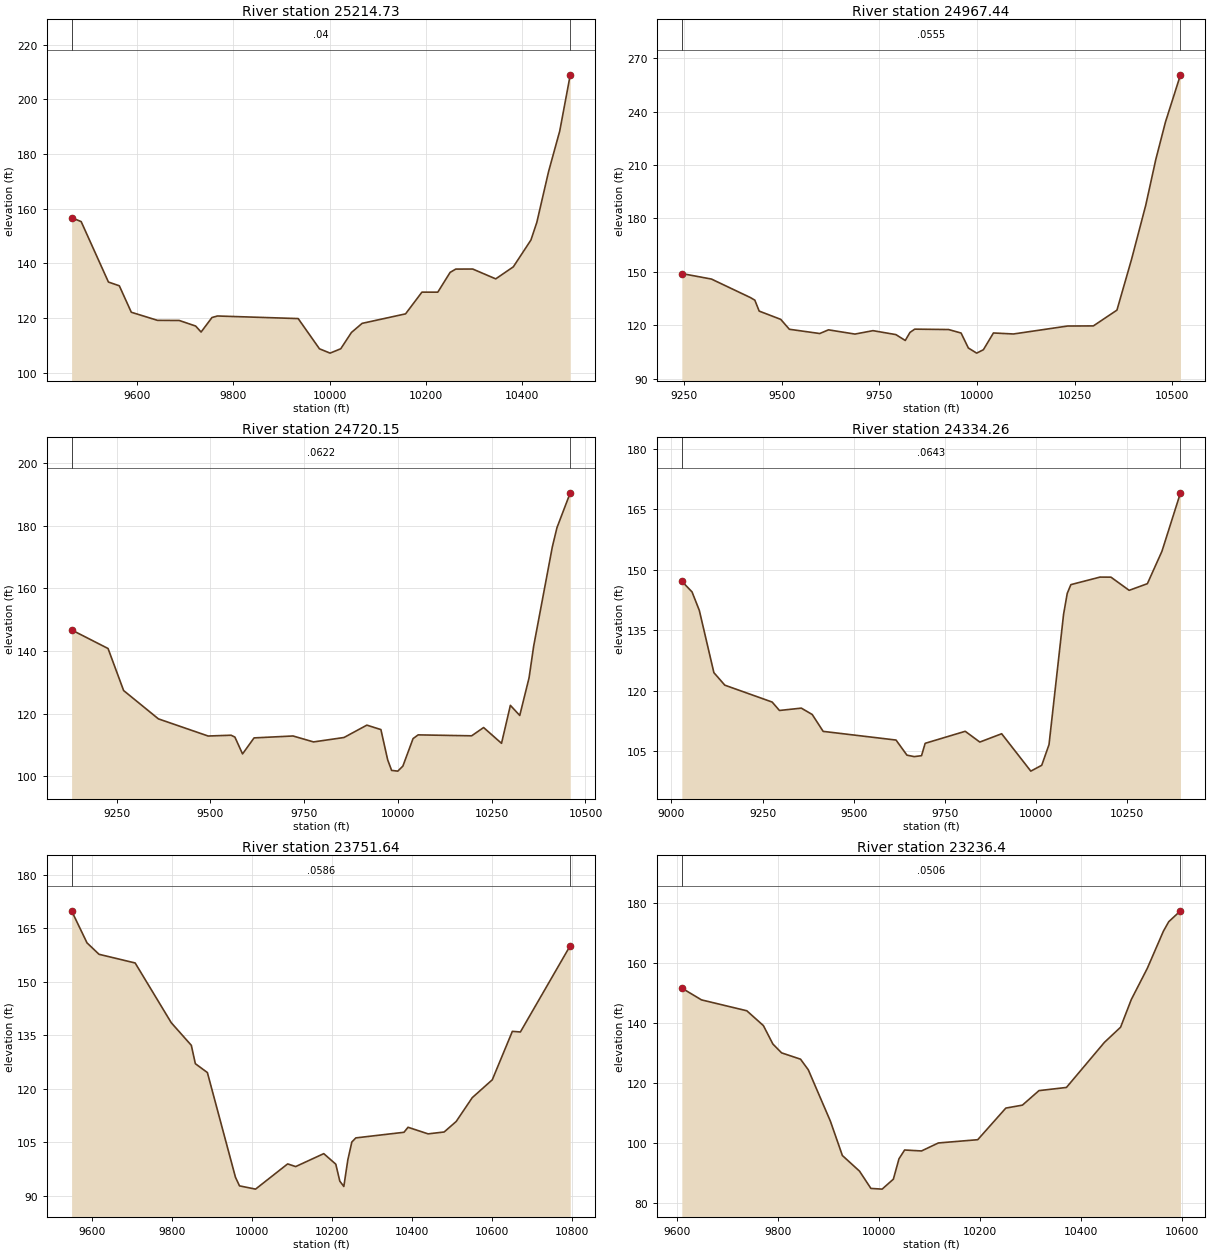
Type RM Length L Ch R = 1 ,25214.73,247.291900,247.291900,247.291900
XS GIS Cut Line= 6
862467.430340905842233.051151871862758.727131707842078.661055218
863023.043592735841951.032891054 863119.20682031841899.754488457
  863227.5207922841833.163654373  863371.4625464 841731.80773379
#Sta/Elev= 30
9464.487156.73599484.372155.30139540.961133.23189563.596131.84999588.449122.1947
 9642.82119.23169688.091 119.1879722.045117.15359733.362114.96539755.998 120.269
9767.315 120.8249934.981119.87679979.131108.843110001.21107.258610023.38108.8557
10045.55114.806210067.72118.130310157.93121.602710191.93129.536410224.87129.5283
10250.45136.755210262.19137.959310297.41137.978110345.15134.385610381.71138.7845
10418.27148.586110430.46155.008410454.84173.548210478.07188.406810499.91208.9221
#Mann= 3 , 0 , 0
9464.487    0.04       09464.487    0.04       010499.91    0.04       0
#XS Ineff= 2 , 0
       0                10141.91       0
Bank Sta=9464.487,10499.91
Exp/Cntr=0.3,0.1

Type RM Length L Ch R = 1 ,24967.44,247.291900,247.291900,247.291900
XS GIS Cut Line= 6
862417.637316678842573.323368515862799.507039215842385.496506131
862889.862174446842332.892220039863033.382414319842230.658894697
863288.696191925842028.158528011863485.799942138841882.127402461
#Sta/Elev= 30
9243.523149.03629319.399145.94469419.576135.51359430.631134.07329441.735127.9414
9496.961123.3052 9519.07117.73439596.921115.34369619.313117.41159687.071115.0401
9733.356116.95539791.942114.74049816.047111.4341  9828.1115.95749840.153117.8006
9926.977117.58749959.013115.62229977.669107.2163    9999104.3317 10016.2106.2463
 10041.9115.653810093.31115.089210232.05119.556210297.95119.617610358.37128.4921
10395.71 156.95210432.34187.582110457.93 213.13810482.73234.191810521.16260.6771
#Mann= 3 , 0 , 0
9243.523  0.0555       09243.523  0.0555       010521.16  0.0555       0
#XS Ineff= 2 , 0
       0                10274.56       0
Bank Sta=9243.523,10521.16
Exp/Cntr=0.3,0.1

Type RM Length L Ch R = 1 ,24720.15,385.884200,385.884200,385.884200
XS GIS Cut Line= 6
862452.957077889842683.437581372862976.568163255842555.819092811
863092.463422478842509.647062975863179.950579838842444.598870817
863377.317606764842242.207728483863594.289178519842076.629750648
#Sta/Elev= 30
  9129.6146.69229226.808140.75899268.356127.33499361.158118.28949493.693112.8185
9554.863113.07099565.058112.47739585.447107.10149616.172 112.218 9720.11112.8305
9774.719 110.9349856.037112.34569916.974116.29449954.422114.8742 9972.51105.2043
9982.976101.83859999.467101.608910013.02103.211710040.19111.993510053.77113.1834
10196.38112.884110228.28115.525510276.07110.485810299.69122.608510324.68119.3813
10349.49131.3867 10361.9141.577810411.51173.168710423.88179.330510459.38190.4645
#Mann= 3 , 0 , 0
  9129.6  0.0622       0  9129.6  0.0622       010459.38  0.0622       0
#XS Ineff= 2 , 0
       0                10357.84       0
Bank Sta=9129.6,10459.38
Exp/Cntr=0.3,0.1

Type RM Length L Ch R = 1 ,24334.26,582.619400,582.619400,582.619400
XS GIS Cut Line= 2
862456.962762308842706.777626114863825.890304629842690.107887064
#Sta/Elev= 30
9028.356147.17529056.395144.53079076.397139.94659116.399124.49519146.402121.3865
9276.411117.19429296.413115.10449356.417115.6862 9386.42114.10399416.422109.9174
9616.437107.76519646.439104.0184 9666.44103.65589686.442103.88329696.442106.9542
9806.451109.93639846.454107.26659906.458109.33049986.464100.052710016.47101.5031
10036.47106.637910076.47138.995510086.47 144.15710096.47146.336810176.48148.2065
10206.48148.191510256.48144.921410306.49146.569810346.49154.615510397.38169.1199
#Mann= 3 , 0 , 0
9028.356  0.0643       09028.356  0.0643       010397.38  0.0643       0
#XS Ineff= 2 , 0
       09405.922                       0
Bank Sta=9028.356,10397.38
Exp/Cntr=0.3,0.1

Type RM Length L Ch R = 1 ,23751.64,515.247700,515.247700,515.247700
XS GIS Cut Line= 2
862606.609648629 843155.14247088863849.287457774843037.207114707
#Sta/Elev= 30
 9548.34169.82949586.903160.85989617.038157.65829707.442 155.2299797.847138.4988
9848.071132.16279858.116127.02679888.251124.54499958.56595.21814 9968.6192.81571
10008.7991.9033210089.1598.9664610109.24 98.219910179.55101.838110209.6998.88841
10219.7394.1405510229.7892.6469310239.82100.107910249.87105.103510259.91106.2479
10380.45107.8227 10390.5109.224610440.72107.3774 10480.9107.901510511.04110.8438
10551.22117.509710601.44 122.52510651.67136.084210671.76135.9066 10796.6160.0785
#Mann= 3 , 0 , 0
 9548.34  0.0586       0 9548.34  0.0586       0 10796.6  0.0586       0
#XS Ineff= 2 , 0
       0                10351.39       0
Bank Sta=9548.34,10796.6
Exp/Cntr=0.3,0.1

Type RM Length L Ch R = 1 , 23236.4,247.291900,247.291900,247.291900
XS GIS Cut Line= 6
863093.202264058843669.586776266863285.690144919843532.778014003
863398.142766213843465.754667186863641.771128473843345.900619335
 863741.75818556843301.436923719863966.898511474843217.625983812
#Sta/Elev= 30
9608.975151.67449647.952147.75739737.763144.13199770.659139.19269789.529 133.043
9806.784130.10679844.283128.00939859.655124.47619903.515107.34729927.19795.93441
9961.21990.718059983.744 84.973610005.9684.7394410028.2688.0551410039.4194.83822
10050.5697.7664610084.0197.4497910117.45  100.1110195.49101.196310251.17111.7242
10284.01112.705510316.84117.5394 10371.3118.596410446.56133.605410478.62138.6506
10499.84147.865210531.67158.285610563.49170.6327 10574.1173.793410597.34177.4095
#Mann= 3 , 0 , 0
9608.975  0.0506       09608.975  0.0506       010597.34  0.0506       0
#XS Ineff= 2 , 0
       0                               0
Bank Sta=9608.975,10597.34
Exp/Cntr=0.3,0.1

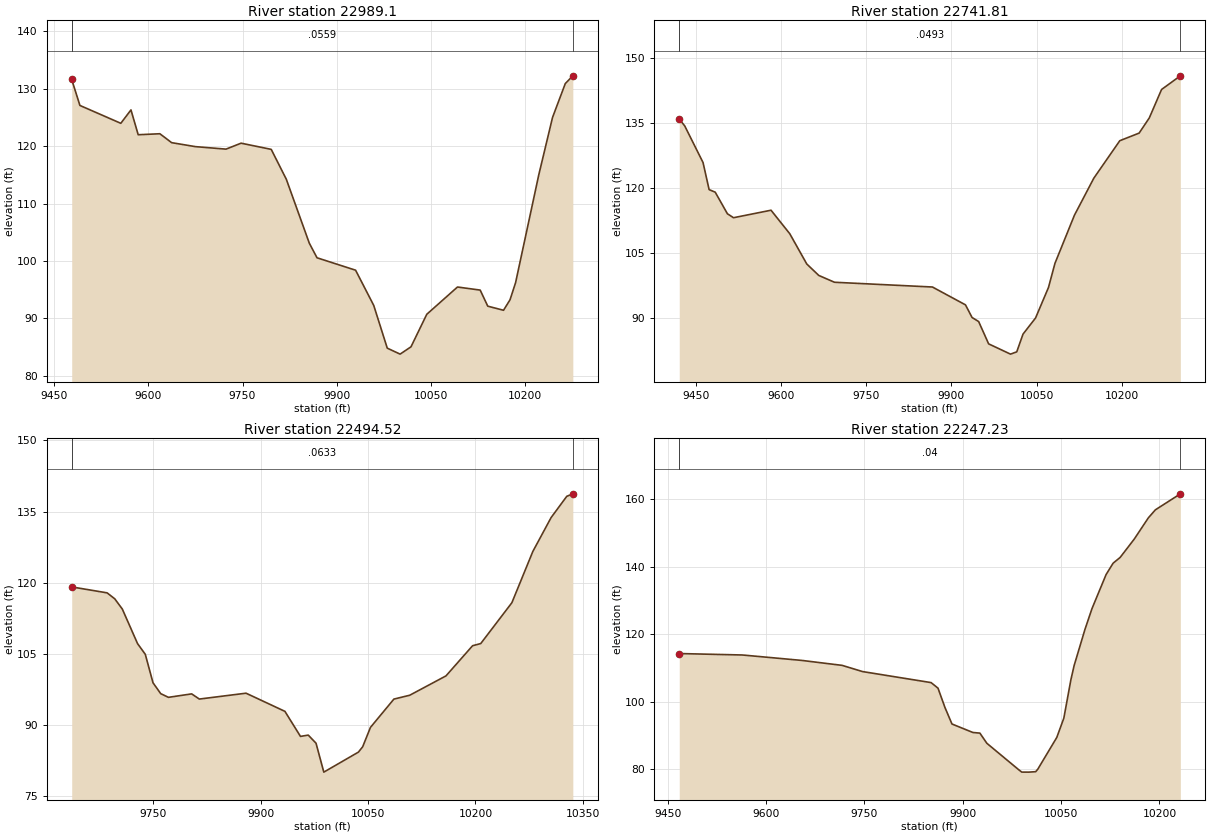
Type RM Length L Ch R = 1 , 22989.1,247.291900,247.291900,247.291900
XS GIS Cut Line= 6
863101.459443725843950.999505886863174.249699641843913.241870036
863317.254179176843828.123651452863487.960337931843710.450210652
863588.408782073843633.404111747  863771.3013684843519.082094955
#Sta/Elev= 30
9477.927131.62979490.956127.10319556.109123.98639572.302126.32239583.813 121.994
9618.347 122.1679637.081120.61349675.177119.91759723.723119.48479747.682120.5211
9795.717119.44319819.735114.23449856.367103.08679868.655100.54099930.09798.37498
9959.01992.229589980.52784.78787   1000183.7429910018.3585.0187310043.4890.68888
10092.3895.4436810128.5594.90794 10140.692.1072410165.7291.3886610176.1193.22644
10184.9596.2039510221.93 115.02610243.79125.0077 10264.1130.912410276.12132.2655
#Mann= 3 , 0 , 0
9477.927  0.0559       09477.927  0.0559       010276.12  0.0559       0
#XS Ineff= 2 , 0
       0                               0
Bank Sta=9477.927,10276.12
Exp/Cntr=0.3,0.1

Type RM Length L Ch R = 1 ,22741.81,247.291900,247.291900,247.291900
XS GIS Cut Line= 6
863175.992264063844124.584457944863374.084768435844039.230766126
863495.287410441 843974.20316586863660.049936902843875.998957507
863736.245821334 843840.56008554863959.361262243843719.642460612
#Sta/Elev= 30
9420.371135.80169430.047134.21319462.272125.77429473.014119.51429483.756118.9217
 9505.24113.94389515.981113.02989582.084 114.7599615.137109.33249645.112102.3445
9666.26499.704569693.94498.134759866.50697.036579924.71492.919329936.35689.99736
9947.93789.068149965.51883.9164710004.0281.5480510015.0682.07518 10026.186.16653
10048.1889.8864710070.9896.93007 10082.4102.503610116.68113.601810150.95122.1742
10196.65130.803110230.71132.558110248.64136.069310270.21142.618810303.34 145.776
#Mann= 3 , 0 , 0
9420.371  0.0493       09420.371  0.0493       010303.34  0.0493       0
#XS Ineff= 2 , 0
       0                               0
Bank Sta=9420.371,10303.34
Exp/Cntr=0.3,0.1

Type RM Length L Ch R = 1 ,22494.52,247.291900,247.291900,247.291900
XS GIS Cut Line= 6
863448.557002924844225.691197474863533.386888237844194.921867727
863613.480116804844162.461457173863836.393975463844067.866100202
864054.863341626843969.036535304864092.759286348843952.411818925
#Sta/Elev= 30
9636.126 119.135 9685.53117.88649696.167116.64099706.805114.47059728.104107.1822
9738.894104.93079749.68498.930559760.47596.637489771.26595.865169803.63596.59283
9814.43695.500499879.62396.738289933.94692.909099955.67587.629949966.53987.90324
9977.40486.194659988.26880.1012710036.65  84.32310042.5785.4504410053.4389.53117
10086.1695.4926810108.2996.3068410158.94100.387110196.09106.742810207.47107.1984
10250.97115.804110280.25126.609210305.79133.758910327.63138.226810336.11138.7563
#Mann= 3 , 0 , 0
9636.126  0.0633       09636.126  0.0633       010336.11  0.0633       0
#XS Ineff= 2 , 0
       0                               0
Bank Sta=9636.126,10336.11
Exp/Cntr=0.3,0.1

Type RM Length L Ch R = 1 ,22247.23,284.404400,284.404400,284.404400
XS GIS Cut Line= 6
863378.963551411844430.223671976863470.988542971844424.573536935
863546.572995891844414.942099936 863680.62971834844384.457242736
863913.012684655844303.205774689864110.511876691844225.987101812
#Sta/Elev= 30
9467.749114.24899563.991113.82289654.908112.21239716.244110.74859747.222108.9166
9851.819105.65129862.367104.00929873.01198.263349883.65593.399559915.58790.88347
9926.23190.699349936.87587.687429985.43679.864629990.094 79.161710000.7479.15296
10011.3879.2843310014.6680.0596610043.5189.4156310054.25 95.124710064.99106.4586
 10069.9110.657710086.46121.3877 10097.2127.553910118.67137.614910129.41140.9942
10140.15142.699610161.62148.1206 10183.1   154.410193.83156.778410231.96161.5235
#Mann= 3 , 0 , 0
9467.749    0.04       09467.749    0.04       010231.96    0.04       0
#XS Ineff= 2 , 0
       0                               0
Bank Sta=9467.749,10231.96
Exp/Cntr=0.3,0.1