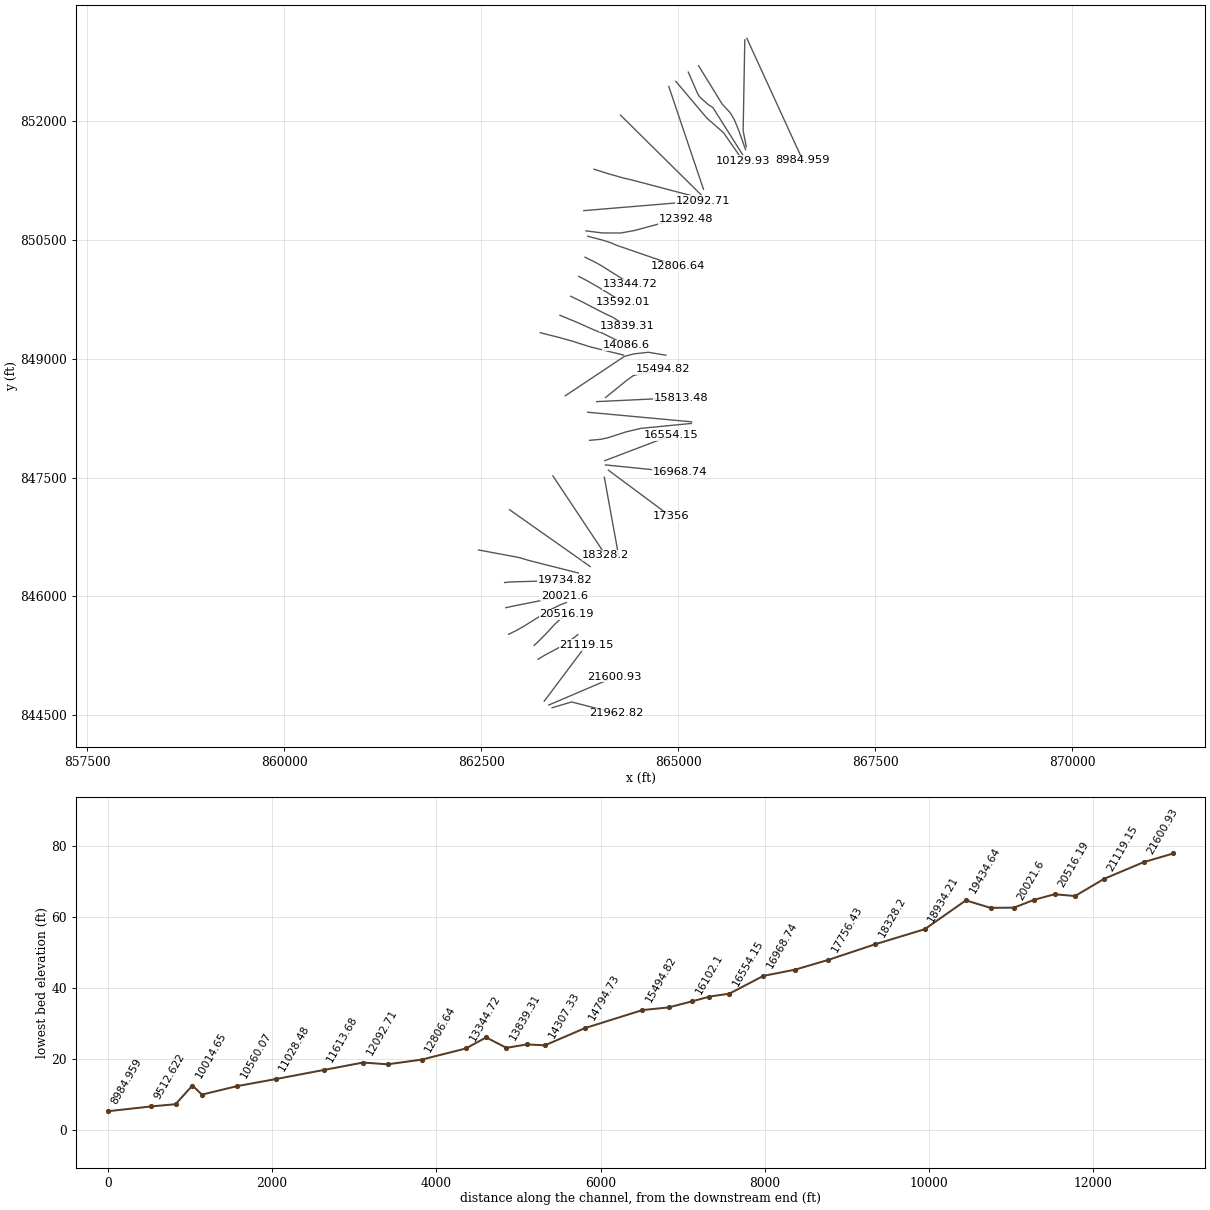
HEC-RAS study 16941_ras.prj: 16941

--- 16941_ras.g01 (geometry) --- (continued)

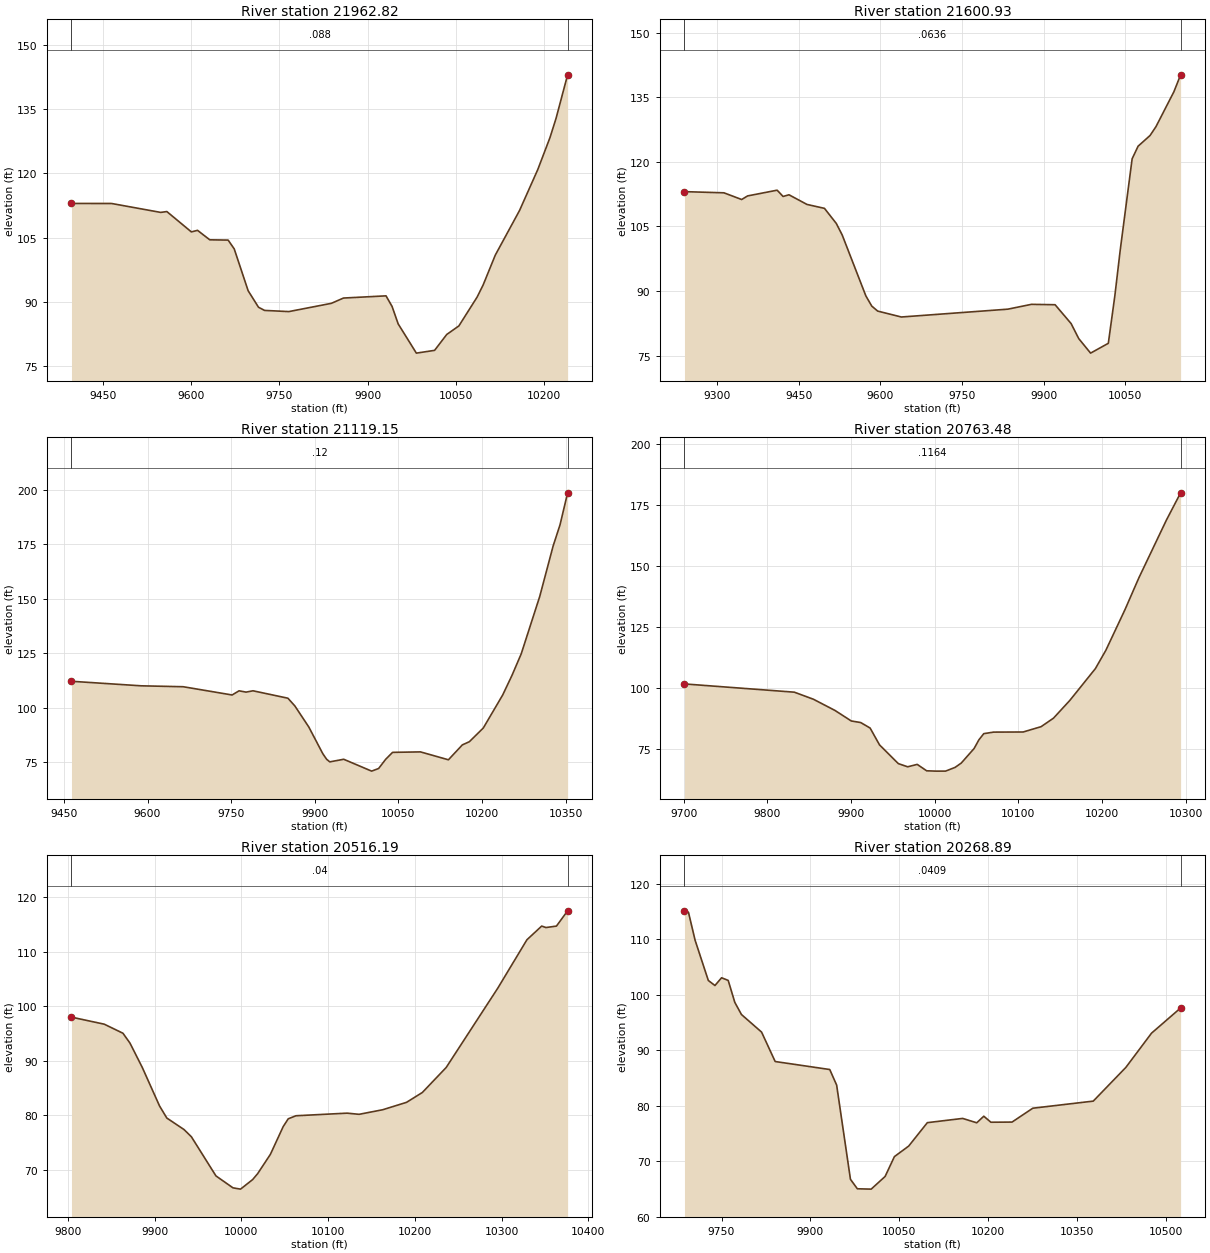
Type RM Length L Ch R = 1 ,21962.82,361.890700,361.890700,361.890700
XS GIS Cut Line= 3
863399.582009232844592.588688651863646.599119905844665.485823804
864214.109002017 844521.52321367
#Sta/Elev= 30
9396.881112.98219465.089112.97889548.499110.89719558.926111.09789600.631106.3447
9611.058106.7123 9631.91 104.4979663.097104.43289673.414102.38299697.07592.61042
9714.681 88.75329724.99888.011159766.26587.738689838.48289.665869859.11590.90034
9931.33291.413229941.64988.943519951.96684.874789982.91678.0390410013.8778.68522
 10034.582.3905410055.1384.3893110086.0891.11062 10096.493.9611910117.03100.9309
 10158.3111.363610189.25120.912410209.88128.3416 10220.2132.826610239.92143.0231
#Mann= 3 , 0 , 0
9396.881   0.088       09396.881   0.088       010239.92   0.088       0
#XS Ineff= 2 , 0
       0 9776.42                       0
Bank Sta=9396.881,10239.92
Exp/Cntr=0.3,0.1

Type RM Length L Ch R = 1 ,21600.93,481.782900,481.782900,481.782900
XS GIS Cut Line= 3
863358.260964821844626.860680017864085.990675028844936.442466644
864196.268570652844985.956014598
#Sta/Elev= 30
9239.919113.08929312.446112.81759345.048111.26089355.915112.09439410.252113.4279
9421.119111.96999431.986112.35829465.076110.1176 9497.19109.20629518.924105.7042
9529.791103.0176 9573.2688.871039584.128  86.5019594.99585.339239638.46483.96635
9834.07485.785799877.54386.906999921.01286.81792 9950.4482.438129964.48178.94186
9986.21675.5744610018.8277.8573410030.76 88.853110040.6499.4644810062.56120.7159
10073.52123.646510095.45126.125510106.41128.196310139.29136.288510151.64140.2269
#Mann= 3 , 0 , 0
9239.919  0.0636       09239.919  0.0636       010151.64  0.0636       0
#XS Ineff= 2 , 0
       09614.316                       0
Bank Sta=9239.919,10151.64
Exp/Cntr=0.3,0.1

Type RM Length L Ch R = 1 ,21119.15,355.673300,355.673300,355.673300
XS GIS Cut Line= 2
863299.752238035844674.839331371863835.053682244845385.825143237
#Sta/Elev= 30
9463.573112.06599588.677109.98289664.053109.56469751.675105.78079764.192 107.691
 9776.71107.09519789.227107.70139851.814104.29959864.332 100.7389889.36791.06699
9914.40178.857099921.18976.321749926.91975.105879951.95476.2936210002.0270.85802
10014.5472.0659110027.0676.2514810039.5879.4676610089.65 79.678710139.7176.05803
10164.7582.9026910177.2784.34394 10202.390.6404810237.08105.7803 10253.7114.7399
10270.33124.661610303.58151.020210327.48174.046410339.99183.891710353.54198.4971
#Mann= 3 , 0 , 0
9463.573    0.12       09463.573    0.12       010353.54    0.12       0
#XS Ineff= 2 , 0
       0                               0
Bank Sta=9463.573,10353.54
Exp/Cntr=0.3,0.1

Type RM Length L Ch R = 1 ,20763.48,247.291900,247.291900,247.291900
XS GIS Cut Line= 6
863221.892677635845204.984548096863298.545810541845251.678069095
  863530.3642481845375.195495322863570.822217865845400.079987614
  863609.0777379845426.115009975863725.958786232845515.331297956
#Sta/Elev= 30
9700.828101.70169832.18198.323919855.00395.431729880.88690.827129900.28886.52958
9911.55385.884539922.81783.637189934.08276.729239956.612 69.05579967.77467.76529
9979.14168.752089990.40666.1257210001.68 65.991110013.0666.0007910024.4367.52354
10031.8669.3122710047.1775.2594810052.8678.7842510058.7181.3367610070.4581.96843
10105.8282.0153310127.2984.2021710142.1187.6875310161.6994.9765810192.23107.9927
10204.81115.553910227.61132.151410244.09145.085410277.06168.759210294.08179.9566
#Mann= 3 , 0 , 0
9700.828  0.1164       09700.828  0.1164       010294.08  0.1164       0
#XS Ineff= 2 , 0
       0                               0
Bank Sta=9700.828,10294.08
Exp/Cntr=0.3,0.1

Type RM Length L Ch R = 1 ,20516.19,247.291900,247.291900,247.291900
XS GIS Cut Line= 6
 863170.81908522845379.782036553 863217.38576903845421.560139575
863312.614913144845516.426966597863439.382857878 845652.79751114
 863524.26162388845728.326131135863585.759172108845771.746610447
#Sta/Elev= 30
9804.02198.009989841.78496.722259863.37695.062769871.45693.262959885.62588.81352
 9905.5681.748639913.96379.52757 9933.7977.419759942.30276.09547 9970.64 68.9232
9990.25166.739619998.97966.5019810012.9768.2536210018.7569.3440110033.4472.88016
10048.1777.95346   1005479.38564 10062.979.9427410121.8280.4205510135.7280.20676
10162.9681.0468110190.41 82.401410208.6584.2051110236.13 88.784510295.67103.3265
10329.25112.184510346.27114.693210351.21114.426710363.29114.689610376.18117.4877
#Mann= 3 , 0 , 0
9804.021    0.04       09804.021    0.04       010376.18    0.04       0
#XS Ineff= 2 , 0
       0                               0
Bank Sta=9804.021,10376.18
Exp/Cntr=0.3,0.1

Type RM Length L Ch R = 1 ,20268.89,247.291900,247.291900,247.291900
XS GIS Cut Line= 6
  862848.9851053845520.129949594862947.742555199845569.338517477
863037.607549637845619.337577474863377.472011404845830.612419586
863502.406890831845891.805903111 863581.26076692845921.105594499
#Sta/Elev= 30
9687.458115.08769694.179114.84329705.351109.81029727.696102.53849738.869101.6328
9750.042103.02579761.214102.55379772.387 98.5936 9783.5696.409199817.54593.23658
9840.43287.939229932.50186.498039944.13483.688799967.40166.721619979.03465.01255
10002.3664.9501910025.8567.2306410041.5370.8071910065.6172.7043610097.0676.92508
10156.5977.68831 10180.476.9013310192.3178.0877510204.21 77.002710239.9377.02975
10274.8979.5268310376.9180.8069210431.9186.8861210475.1193.04099 10524.297.58386
#Mann= 3 , 0 , 0
9687.458  0.0409       09687.458  0.0409       0 10524.2  0.0409       0
#XS Ineff= 2 , 0
       0                10325.25       0
Bank Sta=9687.458,10524.2
Exp/Cntr=0.3,0.1

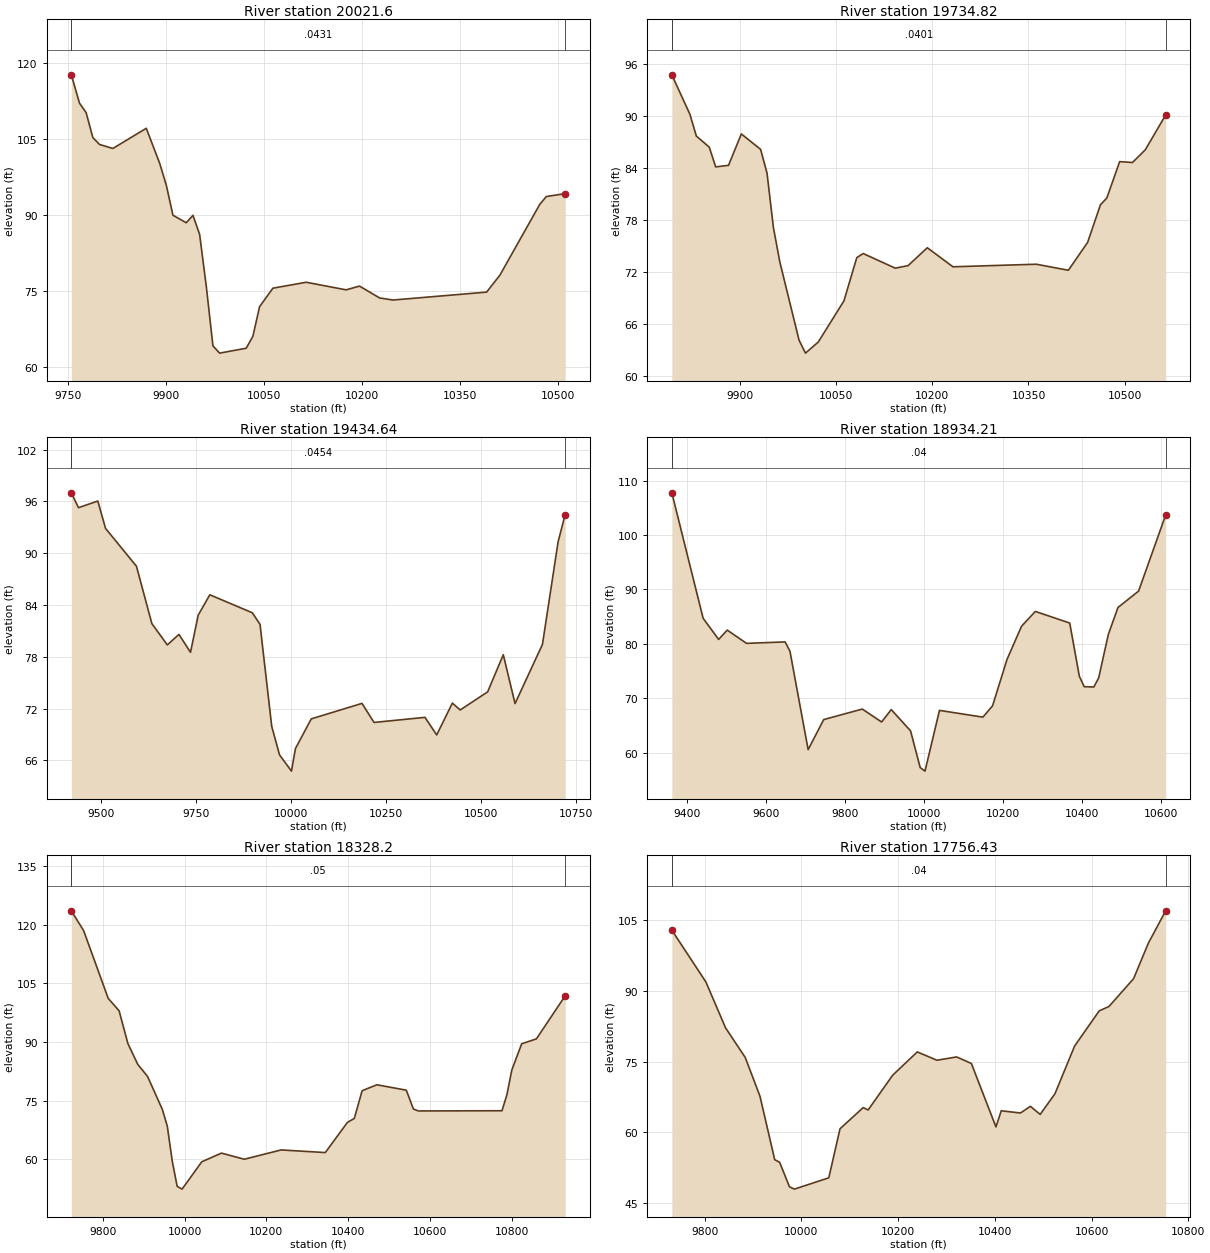
Type RM Length L Ch R = 1 , 20021.6,286.783800,286.783800,286.783800
XS GIS Cut Line= 6
862812.877171379845856.258400686862935.474276598845882.382760767
863220.088450647845938.616952102863444.738809749845987.355496343
863527.387548331 846001.33138334863553.654938543846004.841390599
#Sta/Elev= 30
 9754.82117.57939767.215112.00769777.439110.11799787.664105.22189797.888103.8541
9818.337103.0615 9869.46107.03629889.884100.17299900.08295.847599910.28189.89915
9930.67788.418649940.87689.877289951.07486.147569961.27275.90201 9971.4764.15323
9981.66962.7177910022.4463.6851110032.63 66.053610042.8271.86912 10063.275.51928
10114.1576.6879710175.3175.1947710195.7875.9298710226.4873.5944410246.9473.18599
 10390.274.7416910410.5778.0860410471.4292.0089510481.5693.5870310510.49  94.155
#Mann= 3 , 0 , 0
 9754.82  0.0431       0 9754.82  0.0431       010510.49  0.0431       0
#XS Ineff= 2 , 0
       0                10396.63       0
Bank Sta=9754.82,10510.49
Exp/Cntr=0.3,0.1

Type RM Length L Ch R = 1 ,19734.82,300.175600,300.175600,300.175600
XS GIS Cut Line= 5
862796.971169127846173.598355517862862.665150032846180.506015576
862932.364390803846183.304407389863566.216941121846199.897418861
863566.785865832846199.804039171
#Sta/Elev= 30
9793.65694.758379821.83990.206649831.89487.690739852.00586.417679862.04984.13682
9882.06584.315699902.08187.938699932.10486.162389942.10783.435099952.11177.13915
9962.11473.169929992.12564.1423110002.1362.6522610022.1363.9366310062.1568.68186
10082.1673.6655510092.1674.1422810142.1872.4553210162.1872.7452410192.1974.81118
10232.2172.6122510362.2572.9088310412.2772.2127810442.2875.4237710462.2979.75875
10472.2980.55312 10492.384.74562 10512.384.6467710532.3186.1123510564.1190.13248
#Mann= 3 , 0 , 0
9793.656  0.0401       09793.656  0.0401       010564.11  0.0401       0
#XS Ineff= 2 , 0
       0                               0
Bank Sta=9793.656,10564.11
Exp/Cntr=0.3,0.1

Type RM Length L Ch R = 1 ,19434.64,500.430900,500.430900,500.430900
XS GIS Cut Line= 6
862466.477672399846585.048067129862967.581637035846492.167285082
863002.490242161846483.304902869863014.554515128846479.671535081
863106.096340989846452.277404506863733.089464282846294.049904967
#Sta/Elev= 30
9421.78397.003499440.62195.283149491.47396.052729511.81392.883269593.17688.50178
9633.857 81.84829674.53879.386479705.04980.60215 9735.5678.528819755.90182.84075
9786.41285.191339898.28683.109759918.62681.766689949.39369.952279970.05866.64413
10001.3864.7644810011.8267.3748810053.5770.8194310187.07 72.610610218.8570.40436
10352.9270.9931910383.8768.9597110425.1272.6433410445.7571.8501510517.9473.94333
 10559.278.2488910590.1472.5901510662.3379.4409610703.5891.3389710722.2494.48911
#Mann= 3 , 0 , 0
9421.783  0.0454       09421.783  0.0454       010722.24  0.0454       0
#XS Ineff= 2 , 0
       0                10551.89       0
Bank Sta=9421.783,10722.24
Exp/Cntr=0.3,0.1

Type RM Length L Ch R = 1 ,18934.21,606.011000,606.011000,606.011000
XS GIS Cut Line= 2
862860.173438434847092.978478409863883.973908973846375.642966662
#Sta/Elev= 30
9361.172107.74779440.32784.705649479.63780.818149501.37982.53199 9550.22 80.0939
9647.90380.363199660.11378.664829706.187 60.57959745.58666.096499843.26868.02625
 9892.1165.649329916.53167.931359965.37264.027569989.79357.28487   10002 56.6258
10038.6367.7821910148.5366.5432410172.9568.6178110209.5877.1439810246.4283.25157
10281.2885.9612910368.3183.8270510392.7374.0424310404.9472.1385710429.3672.08282
10441.5873.73979   1046681.7232710490.4286.6809610542.6889.7015510611.27 103.688
#Mann= 3 , 0 , 0
9361.172    0.04       09361.172    0.04       010611.27    0.04       0
#XS Ineff= 2 , 0
       0                10312.25       0
Bank Sta=9361.172,10611.27
Exp/Cntr=0.3,0.1

Type RM Length L Ch R = 1 , 18328.2,571.771700,571.771700,571.771700
XS GIS Cut Line= 2
863410.137513355847519.923441805864080.770549804846516.553770552
#Sta/Elev= 30
9723.509 123.5759753.487118.50899813.627101.15959840.23497.989459861.73989.58781
9885.79584.293439909.85181.165979945.93572.736359957.96368.461329969.99159.56931
9982.019 53.08299994.04752.3494210042.1659.3415210090.2761.5679210146.1660.00001
10236.1462.3803810344.1161.70702 10398.169.4190610415.0370.4494910434.0977.53587
10470.0979.0531610542.0777.6732710559.3672.8579710571.3972.3551310775.8772.41199
 10787.976.5021910799.9282.8326510823.9889.5339810860.0690.8098510930.36101.8318
#Mann= 3 , 0 , 0
9723.509    0.05       09723.509    0.05       010930.36    0.05       0
#XS Ineff= 2 , 0
       0                10465.61       0
Bank Sta=9723.509,10930.36
Exp/Cntr=0.3,0.1

Type RM Length L Ch R = 1 ,17756.43,400.430300,400.430300,400.430300
XS GIS Cut Line= 2
864062.418299822847504.238765097864246.198293453846499.707017916
#Sta/Elev= 30
9732.221102.90419802.609 91.90729843.27382.165679883.93775.884839914.435  67.657
9944.93354.173529955.09953.627369975.43148.425619985.59647.9261210056.7650.32617
10079.9760.7423310127.9265.2336110138.09 64.733910188.9272.1188710239.7577.05592
10280.4175.2889510321.0775.9910310351.5774.60524 10402.4 61.135710413.3764.55965
10453.2364.0897110473.5665.50265 10493.9 63.7905 10524.568.1835610565.06 78.3023
10615.89 85.766310636.2286.7110510687.0592.6058310717.55100.140710753.43  107.01
#Mann= 3 , 0 , 0
9732.221    0.04       09732.221    0.04       010753.43    0.04       0
#XS Ineff= 2 , 0
       0                10225.57       0
Bank Sta=9732.221,10753.43
Exp/Cntr=0.3,0.1

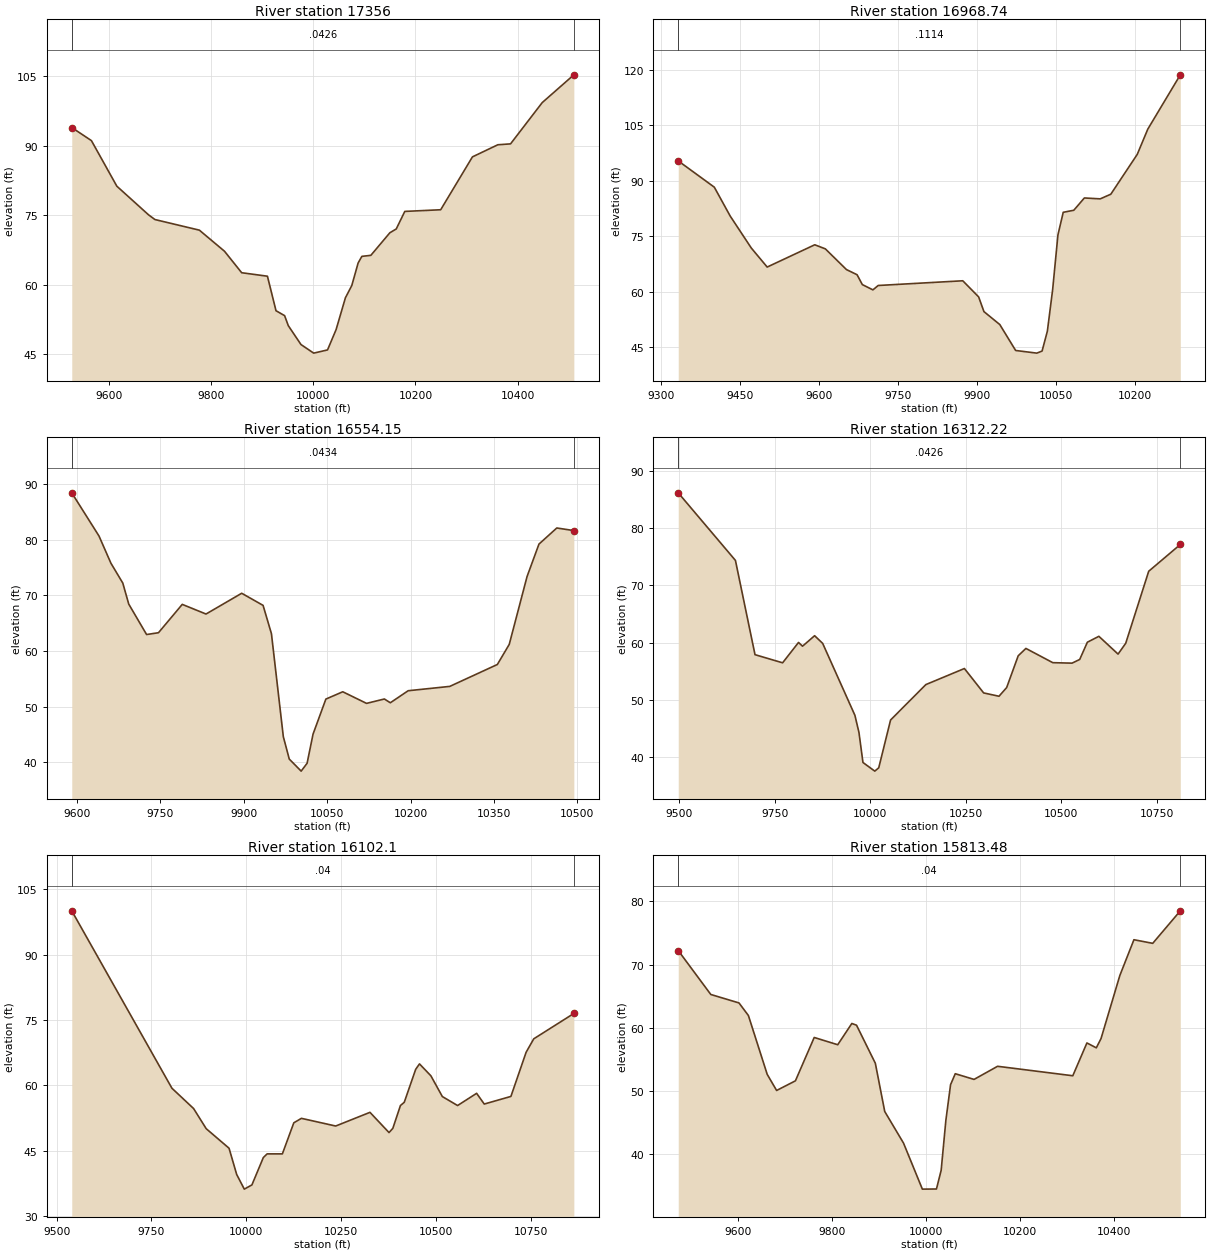
Type RM Length L Ch R = 1 ,   17356,387.259900,387.259900,387.259900
XS GIS Cut Line= 2
864114.049239155 847592.87851255864904.678808822 847008.12346091
#Sta/Elev= 30
9526.78193.934719565.27791.105249615.02981.263869677.21975.066389689.657 74.0532
9776.72271.761129825.91867.206369859.55262.563259910.003 61.8125 9926.8254.35369
9943.63753.292969950.85351.131229975.72947.04895 10000.645.1925510027.7245.88397
10044.5450.2859210062.7957.1579110075.2359.7895710087.6764.6730210094.9966.10041
10112.5566.3172510149.8671.20131 10162.372.0181810179.0775.8095510249.3676.16855
10311.5587.59207 10361.390.2105310386.1890.4030410448.14 99.308610510.16105.3203
#Mann= 3 , 0 , 0
9526.781  0.0426       09526.781  0.0426       010510.16  0.0426       0
#XS Ineff= 2 , 0
       0                               0
Bank Sta=9526.781,10510.16
Exp/Cntr=0.3,0.1

Type RM Length L Ch R = 1 ,16968.74,414.587100,414.587100,414.587100
XS GIS Cut Line= 2
864076.745826147847659.109281864865026.473530781847563.925537257
#Sta/Elev= 30
9332.15595.356399400.75188.255459430.90180.465789471.10271.814159501.25266.68183
9591.703 72.69779611.80371.597259652.00365.996249672.10464.613649682.15461.94243
9702.25460.517029712.30461.702159873.10562.974779903.25658.622539913.30654.65157
9943.45651.155079973.60644.1476910013.8143.4332610023.8643.9915910033.91 49.3653
10043.9660.6127310054.0175.3734510064.0681.4711610084.1682.0224910104.2685.34409
10134.41 85.100310154.5186.3575310204.7697.1071710224.86103.940310286.64118.6039
#Mann= 3 , 0 , 0
9332.155  0.1114       09332.155  0.1114       010286.64  0.1114       0
#XS Ineff= 2 , 0
       0                               0
Bank Sta=9332.155,10286.64
Exp/Cntr=0.3,0.1

Type RM Length L Ch R = 1 ,16554.15,241.928000,241.928000,241.928000
XS GIS Cut Line= 2
864069.151579687847713.149713113864913.671893001848032.938896109
#Sta/Elev= 30
9590.68688.443239639.71280.670679661.097 75.79259682.48372.214179693.17668.43737
9725.25562.966069746.64163.289999789.41268.385979832.18466.651799896.34270.38491
9934.77468.207889949.80663.124199971.19244.605069981.88540.5739410003.27 38.4064
10013.9639.8195210024.6645.0618410047.7351.3605310078.1252.6735210120.8950.58692
10152.9751.3758810163.6650.6970310195.7452.8597310270.5953.6408910356.1457.57631
10377.5261.18707 10409.6  73.39610430.9979.2241110463.0782.1208210493.7381.65348
#Mann= 3 , 0 , 0
9590.686  0.0434       09590.686  0.0434       010493.73  0.0434       0
#XS Ineff= 2 , 0
       09894.273                       0
Bank Sta=9590.686,10493.73
Exp/Cntr=0.3,0.1

Type RM Length L Ch R = 1 ,16312.22,210.121200,210.121200,210.121200
XS GIS Cut Line= 6
863876.148057999847969.534737857864020.986518017847983.180860531
864107.493776208848002.091621259864342.473383456848077.259454625
864529.359438485848121.099196225865167.536233906848182.924287511
#Sta/Elev= 30
9497.26486.142739647.00374.347699698.23857.90046 9770.4956.478629812.13160.03313
9822.62659.380019854.27561.209039875.37459.868569959.77147.312519970.32144.33156
9980.815 39.084610011.7937.5781210022.1338.1570110053.1246.5007310145.4852.68051
10246.3655.4826210296.6751.2283510336.9150.6425110357.0352.1663610387.2157.70537
10407.3358.9893410477.7656.5034610528.0356.4214610548.1357.0596610568.2260.07238
10598.3661.10318 10648.657.9995410668.6659.89272 10728.872.4558410811.52 77.1278
#Mann= 3 , 0 , 0
9497.264  0.0426       09497.264  0.0426       010811.52  0.0426       0
#XS Ineff= 2 , 0
       09915.879        10425.62       0
Bank Sta=9497.264,10811.52
Exp/Cntr=0.3,0.1

Type RM Length L Ch R = 1 , 16102.1,288.627100,288.627100,288.627100
XS GIS Cut Line= 2
863852.050816381848324.356921066865170.242576214848203.350235587
#Sta/Elev= 30
9540.097100.00639804.15259.361329861.24354.71394 9894.5350.094829954.783 45.6134
9974.86739.611959994.951  36.24510015.03 37.206710045.1643.47869 10055.244.32092
10095.3744.32156 10125.551.4389310145.5852.4619310235.9650.7032710326.34 53.8359
10376.5549.2018910386.5950.1731510406.6755.3993110416.7256.1410710446.8463.69131
10456.8864.9374310487.0162.1965210517.1457.4517610557.3155.3964810607.5258.19493
 10627.655.7381410697.8957.4837510738.0667.6100310758.1570.6824110863.8376.48895
#Mann= 3 , 0 , 0
9540.097    0.04       09540.097    0.04       010863.83    0.04       0
#XS Ineff= 2 , 0
       0                10459.55       0
Bank Sta=9540.097,10863.83
Exp/Cntr=0.3,0.1

Type RM Length L Ch R = 1 ,15813.48,318.653700,318.653700,318.653700
XS GIS Cut Line= 2
 863965.75410068848458.661953494865033.666958297848508.858096476
#Sta/Elev= 30
9473.16272.209759542.48465.270669602.55163.932159622.57361.945529662.61752.65172
9682.63950.104729722.68351.628859762.727  58.4779812.78257.330659842.81660.68825
9852.827 60.41499892.87154.401119912.89346.781969952.93741.781519992.98134.52108
10023.0134.5414910033.0337.4977810043.0445.3820610053.0551.0201910063.0652.75193
 10103.1 51.853510153.1653.9250910313.3352.4292210343.37 57.611910363.3956.84198
 10373.458.2946210413.4468.2564410443.4873.9183710483.5273.3473210542.25 78.4831
#Mann= 3 , 0 , 0
9473.162    0.04       09473.162    0.04       010542.25    0.04       0
#XS Ineff= 2 , 0
       0                10336.18       0
Bank Sta=9473.162,10542.25
Exp/Cntr=0.3,0.1

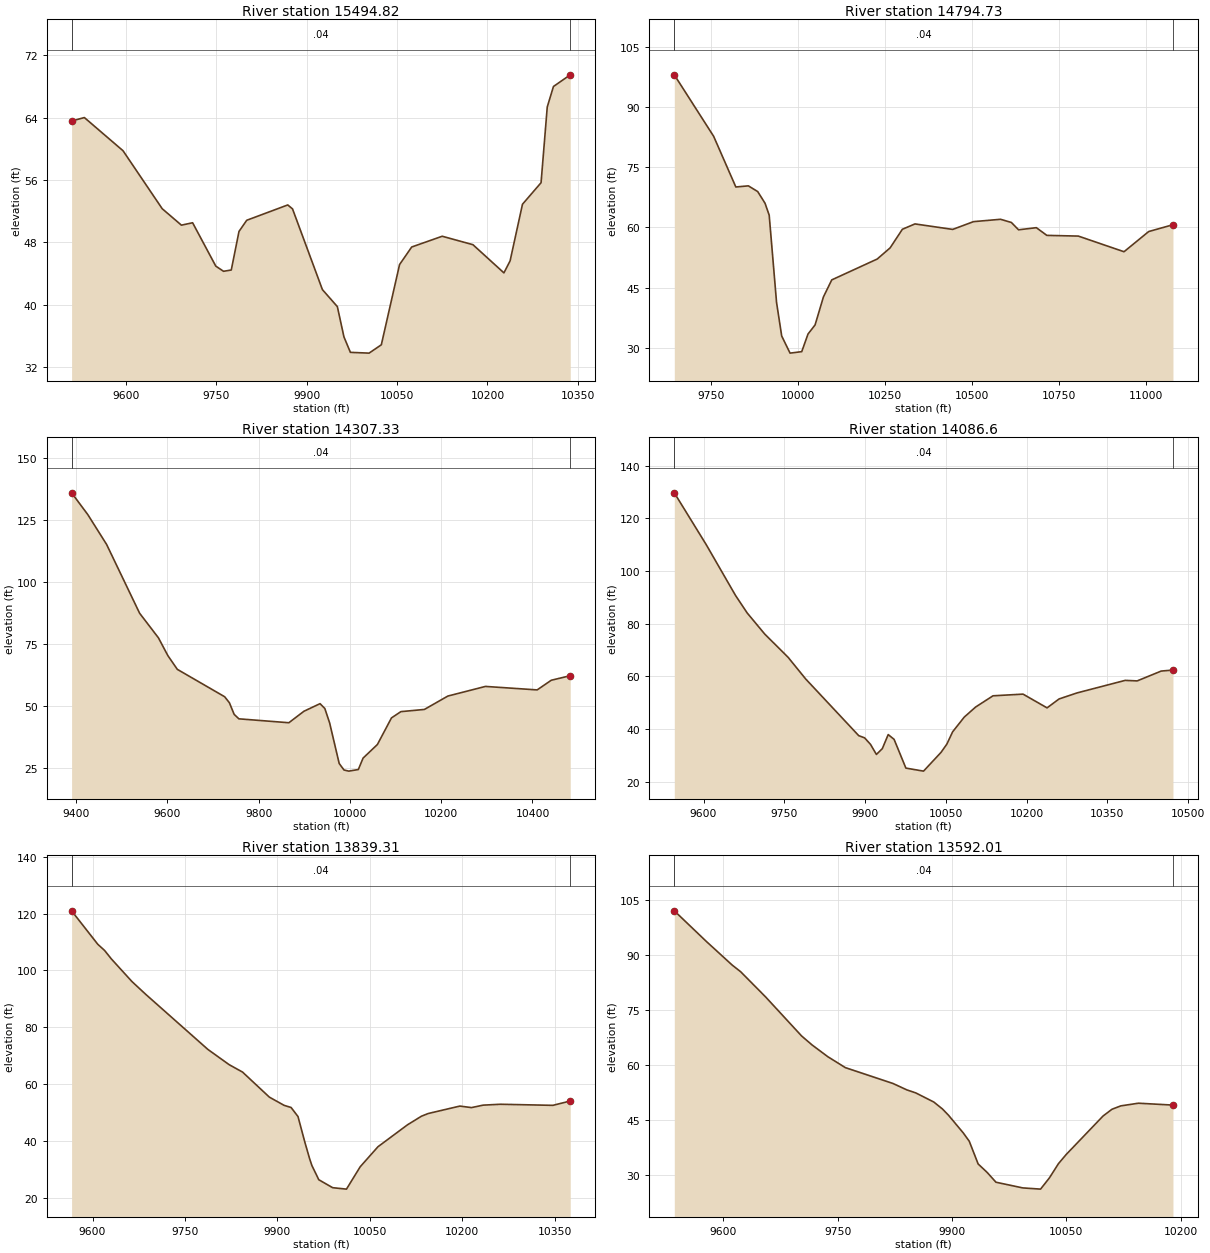
Type RM Length L Ch R = 1 ,15494.82,700.092600,700.092600,700.092600
XS GIS Cut Line= 6
864078.490290471848510.638150653 864341.51862122 848722.43351099
864426.563185537   848784.892091864470.085327953848798.843565894
864628.601928675848824.206054093864802.149189777848865.659609691
#Sta/Elev= 30
 9509.4263.563089530.61664.005049594.81159.746149659.87652.301779691.76550.18988
9710.36150.499869748.87844.930699761.71744.268439774.556 44.43429787.39549.38583
9800.23450.819329868.34952.784979876.253 52.28029925.88241.917899950.69639.73333
9961.69435.833229972.37933.8622510003.3933.7634310023.7134.83424   1005445.13378
10074.1647.3865610124.8148.7676410175.8547.6834610227.2644.0658910237.5445.60641
 10258.152.8780810288.9555.6415110299.2365.3616710309.5167.9912910337.4269.49044
#Mann= 3 , 0 , 0
 9509.42    0.04       0 9509.42    0.04       010337.42    0.04       0
#XS Ineff= 2 , 0
       0                               0
Bank Sta=9509.42,10337.42
Exp/Cntr=0.3,0.1

Type RM Length L Ch R = 1 ,14794.73,487.399300,487.399300,487.399300
XS GIS Cut Line= 5
863567.456267774848532.449427456864317.737820238849029.813368991
864436.878718615849061.162222847864621.166913062849081.821945056
864843.888267249849044.634445056
#Sta/Elev= 30
9644.05598.003049757.26482.685979821.07370.061349857.06670.341449883.95468.92131
9905.05766.014479917.05563.03761 9938.2541.271679953.04832.926999977.04328.66707
10010.6529.0353610028.74  33.42910049.0335.6861610073.0242.6551910097.0246.91223
10227.8352.1109310264.9954.8902310300.2259.5265110336.4260.8563110444.9559.48942
10504.94  61.42710582.7562.0103410613.7761.2174110634.4559.3902810685.6559.92164
10715.8458.00135 10806.457.8278610937.8553.9279811008.8258.9563811078.6660.65685
#Mann= 3 , 0 , 0
9644.055    0.04       09644.055    0.04       011078.66    0.04       0
#XS Ineff= 2 , 0
       0                10494.27       0
Bank Sta=9644.055,11078.66
Exp/Cntr=0.3,0.1

Type RM Length L Ch R = 1 ,14307.33,220.733100,220.733100,220.733100
XS GIS Cut Line= 6
863250.394168238849328.735426732 863509.66103326849263.350418564
863662.370877835849220.080658537 863840.20222998849163.602462581
863897.044490959849146.613877746864305.429632924849046.837469916
#Sta/Elev= 30
9390.329136.10769425.957127.29449467.139115.24569539.32487.527079580.626 77.5795
9601.277 70.40569621.92864.876049725.62953.824599736.02351.401089746.41646.72458
 9756.8144.909049866.27843.331099899.32647.964019934.60851.03029  9945.149.07483
9955.59243.277759976.57626.886519987.067  24.2659997.559 23.805110018.4724.44717
10028.91  29.06210060.2234.5396510091.1345.2875210111.7247.8101410163.1948.69685
10214.6654.0990110297.0157.9875110410.25 56.578510441.13 60.474910482.75 62.3154
#Mann= 3 , 0 , 0
9390.329    0.04       09390.329    0.04       010482.75    0.04       0
#XS Ineff= 2 , 0
       09929.892        10280.32       0
Bank Sta=9390.329,10482.75
Exp/Cntr=0.3,0.1

Type RM Length L Ch R = 1 , 14086.6,247.291900,247.291900,247.291900
XS GIS Cut Line= 6
863499.548025943849548.958828632863705.279221097849464.581438434
863929.911851556849364.790951406863991.097154869849339.891201452
864036.587498981849323.931889767864344.578379087849171.681869417
#Sta/Elev= 30
9545.734129.71899605.308 109.9449659.331  90.7929681.02684.124889713.56976.11979
 9756.9667.302939789.69959.054349888.22637.533779899.17436.688039910.12134.21496
9921.06830.398879932.01632.602879942.963 37.93899953.91136.116559975.80525.21039
10008.58 24.0647   1004131.17094 10051.834.2971410062.5938.9856610084.1144.55963
 10105.348.4000210137.5652.6599410193.34  53.29810237.9648.0798410260.2751.46716
10293.7453.7620810382.9858.5149410405.2958.3162110449.9162.0521510471.7562.43437
#Mann= 3 , 0 , 0
9545.734    0.04       09545.734    0.04       010471.75    0.04       0
#XS Ineff= 2 , 0
       09900.502        10139.74       0
Bank Sta=9545.734,10471.75
Exp/Cntr=0.3,0.1

Type RM Length L Ch R = 1 ,13839.31,247.291900,247.291900,247.291900
XS GIS Cut Line= 6
 863636.78123399849789.034785064863769.392394583849724.771537685
864024.908575977849592.720140733864083.381416954849563.723414816
864164.008408815 849526.94096085864351.213845746849410.076493917
#Sta/Elev= 30
9566.017120.95119608.487109.20359619.599107.01139630.711104.00359664.04896.07564
9686.27391.605669787.23272.227859821.771 66.86119843.54864.248969887.10455.43743
9911.05852.549869922.31551.807429933.57248.614719944.82939.504279952.43833.79639
9956.08631.414929967.34326.394329989.85723.5953710012.2623.0922510034.5930.96045
10063.3937.9948410111.3845.71439   1013448.7328910144.9949.6793210196.3252.29283
10215.2151.7586210234.0952.6228410262.1552.9341110347.3952.5522810375.5854.07735
#Mann= 3 , 0 , 0
9566.017    0.04       09566.017    0.04       010375.58    0.04       0
#XS Ineff= 2 , 0
       0                               0
Bank Sta=9566.017,10375.58
Exp/Cntr=0.3,0.1

Type RM Length L Ch R = 1 ,13592.01,247.291900,247.291900,247.291900
XS GIS Cut Line= 6
863737.549457019850040.075600763863836.057049404 849989.44867029
863989.467058088849902.718609779 864140.46211626849811.349687846
864240.915005216849750.151911666864304.190510316849713.509585254
#Sta/Elev= 30
9535.528101.93869577.63593.577649611.36587.164789622.60885.325169655.32378.45753
9702.50667.817589716.28165.361129736.96962.151059759.94459.177979822.51354.84469
9840.66853.103449852.35652.281339876.05449.788469887.421 47.8813 9895.3746.17048
9914.685 41.35779922.48639.108739934.17432.902779945.86330.620889957.55127.92291
9992.61626.3761510016.0326.0417610027.7429.1298510039.4532.9661210049.6335.47774
10097.9945.97119 10109.747.8182110121.3548.7468110144.46 49.472810189.7548.95796
#Mann= 3 , 0 , 0
9535.528    0.04       09535.528    0.04       010189.75    0.04       0
#XS Ineff= 2 , 0
       0                               0
Bank Sta=9535.528,10189.75
Exp/Cntr=0.3,0.1

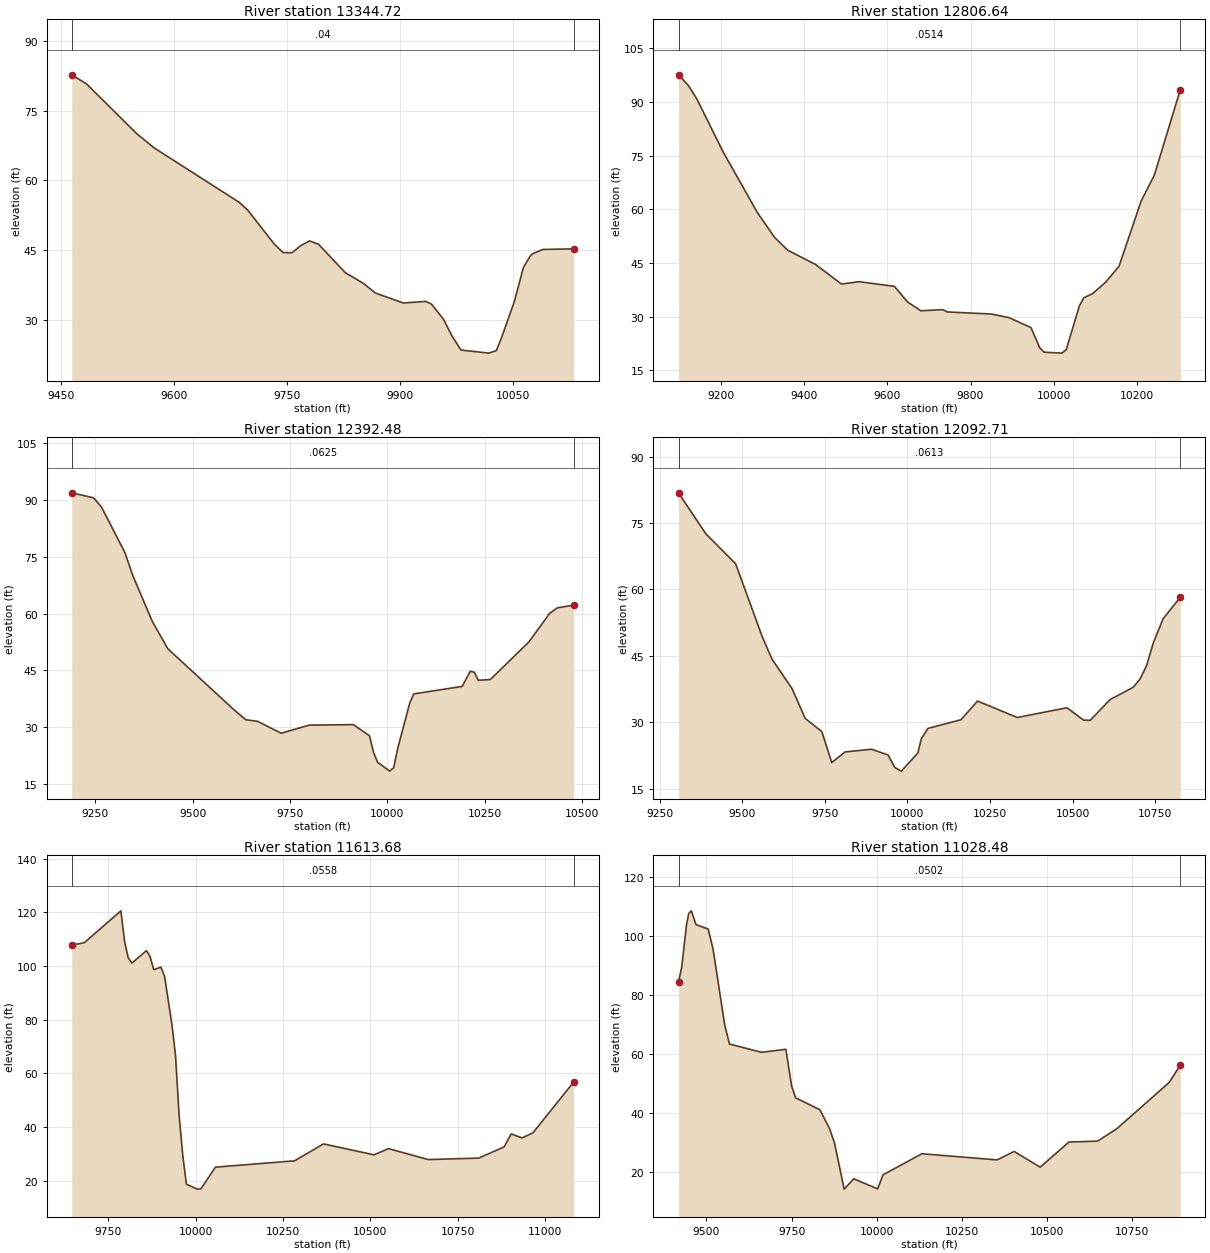
Type RM Length L Ch R = 1 ,13344.72,538.078900,538.078900,538.078900
XS GIS Cut Line= 6
863817.107241927850282.563757088863947.901407215850218.451419902
864025.589677643850174.793034494864310.297026761849996.561631799
864348.025846425 849971.17046518864388.596287019849940.244820731
#Sta/Elev= 30
 9463.7882.699739483.54180.732539550.02370.081029573.17767.017689686.43355.31633
9697.90453.60868    973346.354589744.70444.522749756.407 44.45359768.04845.98938
9779.98747.020249791.86246.305949827.48840.202029851.23837.940379867.61935.82002
9904.701 33.6828 9934.3634.025839942.03133.445769957.82130.245659969.55226.54309
9981.28323.5801810018.45 22.914410028.2623.4582210034.4925.9059110052.2133.96351
10064.2741.3040210073.1143.7041810076.3244.2529710090.1545.1870910130.9845.31052
#Mann= 3 , 0 , 0
 9463.78    0.04       0 9463.78    0.04       010130.98    0.04       0
#XS Ineff= 2 , 0
       0                               0
Bank Sta=9463.78,10130.98
Exp/Cntr=0.3,0.1

Type RM Length L Ch R = 1 ,12806.64,414.166700,414.166700,414.166700
XS GIS Cut Line= 6
863852.327283393 850547.22319763864044.446619062850496.912773677
864121.284419382850472.649046336864156.235807152   850459.869341
 864218.70119084850432.812455405864994.013028215 850166.61942414
#Sta/Elev= 30
9099.21897.615569122.60694.667959143.23790.86959 9205.1376.300799288.03259.17105
9329.86452.117949361.32548.544549427.86744.579549490.34939.088299532.641 39.7489
9617.22538.446659648.94434.078369680.66331.609279733.52831.928419744.10131.28229
9849.83130.702579892.12329.702339944.98826.923759966.13421.263389976.70720.02564
   1001919.7652510029.5720.7335910061.2933.0176610071.8635.2491510093.0136.41988
10124.7339.6562310156.4544.0998610209.3162.2937110241.0369.5257410303.4393.48166
#Mann= 3 , 0 , 0
9099.218  0.0514       09099.218  0.0514       010303.43  0.0514       0
#XS Ineff= 2 , 0
       0                               0
Bank Sta=9099.218,10303.43
Exp/Cntr=0.3,0.1

Type RM Length L Ch R = 1 ,12392.48,299.769600,299.769600,299.769600
XS GIS Cut Line= 6
863829.841047224850614.609988272864039.409734715850588.538207306
 864271.40303561850587.998249178864444.867416542850619.188883299
864877.381593925850735.562596271865096.569502969850764.488662482
#Sta/Elev= 30
9189.03591.814139244.86890.508499265.09888.131639325.44176.102069345.55570.09132
9395.84157.945419435.915 50.69869606.05234.606739636.12731.988639666.40431.57569
9727.02828.436129798.79330.561949912.59230.70416 9954.0127.769579964.36423.38022
9974.71920.7963910005.7718.4436610016.1319.3258810026.4924.4250610057.56 36.4511
10067.9238.80451 10192.2 40.785910212.9144.7632410223.2744.5306510233.6342.39446
10264.58 42.602610363.5552.4937810416.6660.02057 10436.761.4932310478.3262.19773
#Mann= 3 , 0 , 0
9189.035  0.0625       09189.035  0.0625       010478.32  0.0625       0
#XS Ineff= 2 , 0
       0                10081.62       0
Bank Sta=9189.035,10478.32
Exp/Cntr=0.3,0.1

Type RM Length L Ch R = 1 ,12092.71,479.028000,479.028000,479.028000
XS GIS Cut Line= 2
863802.517614206850870.444483615865317.009711982 850995.97201209
#Sta/Elev= 30
 9306.8181.819789389.57572.561189479.88465.785349560.15849.346079590.26144.19771
9650.46737.626739690.604 30.83819740.77527.865269770.878 20.88249811.01523.26841
 9891.2923.892049941.46122.59274 9961.5319.773739981.59818.9398510031.7723.04942
 10041.826.1922310061.8728.5812110162.2230.5558110212.3934.76992 10332.831.05681
10483.3133.2630710533.48 30.463310553.55 30.422310613.7635.10612   1068437.88945
10704.0739.6913110724.1442.74663 10744.247.7884810774.3153.37547 10826.558.21294
#Mann= 3 , 0 , 0
 9306.81  0.0613       0 9306.81  0.0613       0 10826.5  0.0613       0
#XS Ineff= 2 , 0
       0                10235.76       0
Bank Sta=9306.81,10826.5
Exp/Cntr=0.3,0.1

Type RM Length L Ch R = 1 ,11613.68,585.197200,585.197200,585.197200
XS GIS Cut Line= 6
863930.915754524851394.077138133863939.611468307851390.980455578
864098.670505294851340.646463026864314.015242412851279.707634166
864394.672612889851261.974786449865317.591951333851020.338786804
#Sta/Elev= 30
9645.713107.81189681.573108.67519786.461120.57439796.949109.12149807.438103.0463
9817.927101.10239859.534105.73539869.927103.5774 9880.3298.648599901.10699.57893
9911.49996.098889932.28578.307789942.67866.792789953.07144.322949963.464 29.4575
9973.85718.6892910005.0416.8384410015.4316.9462710056.8325.0164810283.5627.39471
10366.2533.6941710510.9729.6179110552.3231.9490910666.0327.8591810810.7528.40925
10883.1132.5610810903.7837.4238310934.7935.93292 10965.837.7996611082.1956.70614
#Mann= 3 , 0 , 0
9645.713  0.0558       09645.713  0.0558       011082.19  0.0558       0
#XS Ineff= 2 , 0
       0                10557.57       0
Bank Sta=9645.713,11082.19
Exp/Cntr=0.3,0.1

Type RM Length L Ch R = 1 ,11028.48,468.407100,468.407100,468.407100
XS GIS Cut Line= 2
864268.304588243852076.080139957865318.129518622851042.836039749
#Sta/Elev= 30
9417.97684.48868 9427.3789.612019441.401103.90889448.028107.78839455.432108.6751
9469.463103.98279505.052102.51099519.30895.730469553.64869.929049567.67963.48025
9661.86860.684869733.14961.696219750.08149.214269761.661  45.2589832.94141.18886
9861.45334.762149875.709 30.00829904.22114.266659932.48217.7581610002.6414.35372
10018.2719.1094510132.3226.2743910353.4124.1784510403.1827.0556710479.6921.71452
10563.8730.2419810648.0630.5515610704.1834.7172410858.5250.4836510890.9756.36068
#Mann= 3 , 0 , 0
9417.976  0.0502       09417.976  0.0502       010890.97  0.0502       0
#XS Ineff= 2 , 0
       0                10532.02       0
Bank Sta=9417.976,10890.97
Exp/Cntr=0.3,0.1

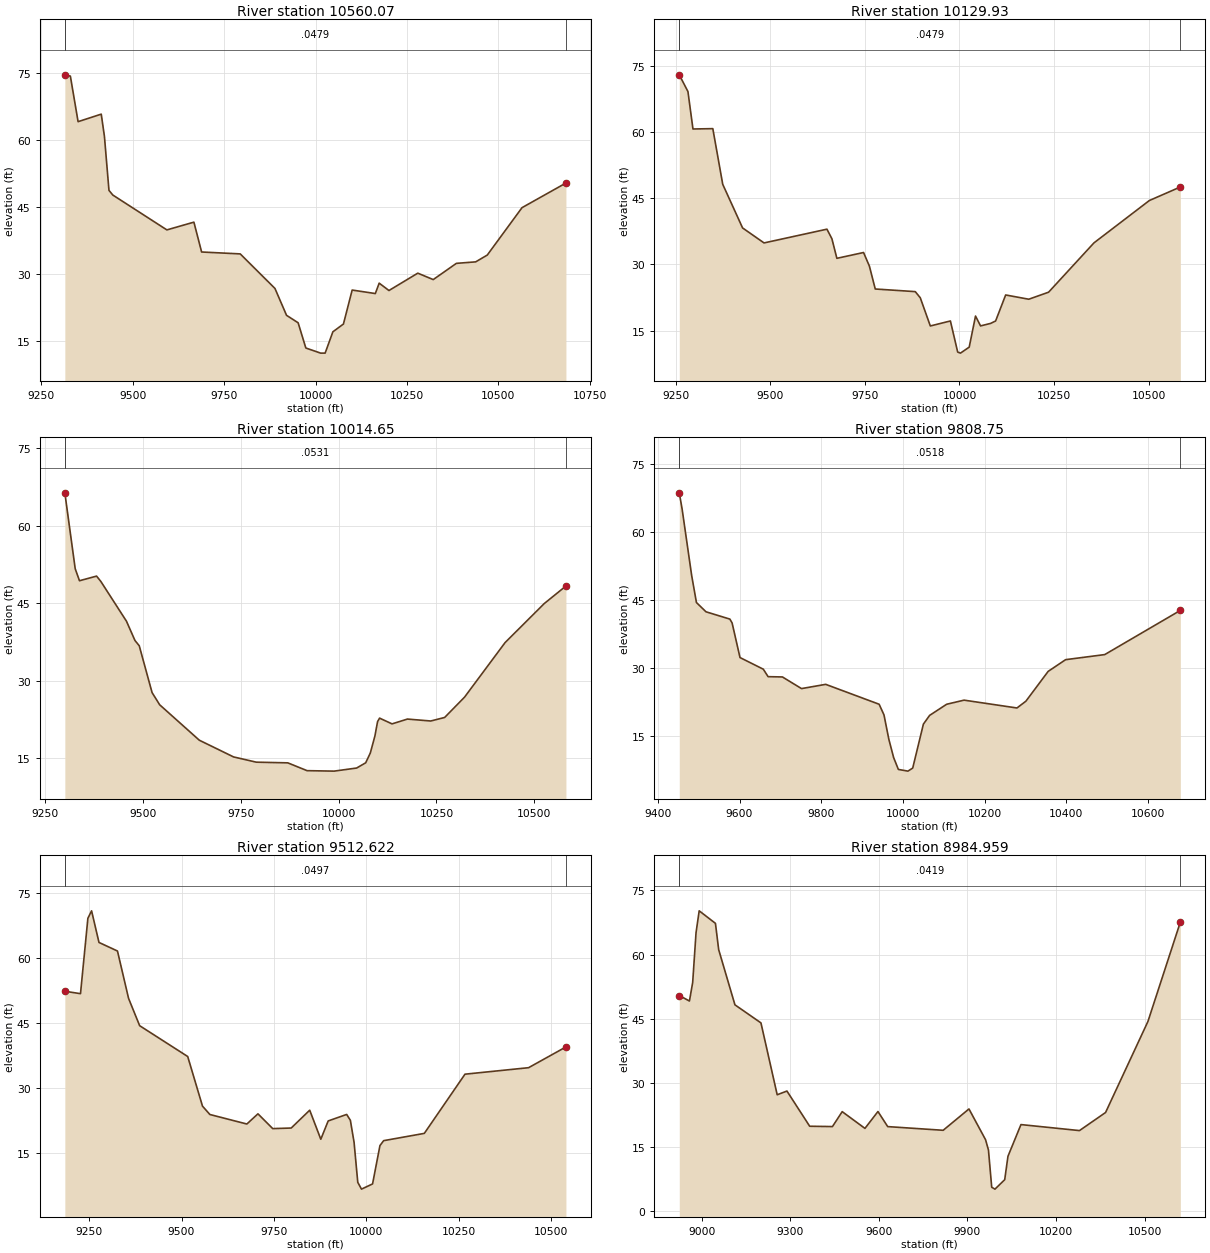
Type RM Length L Ch R = 1 ,10560.07,430.147000,430.147000,430.147000
XS GIS Cut Line= 2
864880.231456823852439.317607053 865320.48101812851141.246674885
#Sta/Elev= 30
9314.19574.506429329.31374.217059350.43264.034229413.78965.714199422.44560.77561
9434.90848.671489445.468 47.6264  9593.339.835679667.21741.566899688.33634.89378
9793.93134.468649888.966 26.74539920.64420.737099952.323 19.07249973.44213.42846
   10014 12.284110026.2412.2904810047.36  17.04710076.2718.7889910100.16  26.386
10163.5125.6065710174.0727.9285910200.8126.2823910279.6730.16266 10321.928.72698
10385.2632.3544810438.0632.6905310469.7434.2098210564.7744.8050310684.8950.31416
#Mann= 3 , 0 , 0
9314.195  0.0479       09314.195  0.0479       010684.89  0.0479       0
#XS Ineff= 2 , 0
       0                10472.71       0
Bank Sta=9314.195,10684.89
Exp/Cntr=0.3,0.1

Type RM Length L Ch R = 1 ,10129.93,115.272400,115.272400,115.272400
XS GIS Cut Line= 4
  864970.1979296852502.587983443865363.164158641852039.035023179
865575.979094949851853.387466979865824.380087523851497.889834856
#Sta/Elev= 30
 9259.7972.91665 9282.6869.125579295.95760.648249348.39560.726679374.61548.11714
9427.05438.237599483.71934.841789649.91837.955929663.02835.786979676.13831.35539
9746.61632.671239762.081 29.58939777.54524.40832  9883.223.81159 9896.4722.42345
 9923.0116.034679976.09117.165989995.32910.1244410002.639.88262410025.7511.23823
10042.4418.2802210055.7116.0472410082.2516.6126410095.5217.1635710122.0623.05515
10183.1122.0917710235.4923.6827810355.3234.8522310501.7244.4488710583.5947.51478
#Mann= 3 , 0 , 0
 9259.79  0.0479       0 9259.79  0.0479       010583.59  0.0479       0
#XS Ineff= 2 , 0
       09744.824                       0
Bank Sta=9259.79,10583.59
Exp/Cntr=0.3,0.1

Type RM Length L Ch R = 1 ,10014.65,205.904300,205.904300,205.904300
XS GIS Cut Line= 6
865127.968887455852619.284028615865240.894941776852360.817018551
865270.739679648852306.853909141865379.836129226852210.557973554
865440.947397755852171.441909599 865824.98553162851564.104222325
#Sta/Elev= 30
9300.07966.343139326.57951.640159337.49249.317899381.14350.216729392.05649.18629
9457.53341.488419479.35837.743459490.27136.726559523.00927.666839542.43725.30167
9643.80418.437529731.357 15.20219789.41914.186479869.92814.053379919.24712.54165
9988.38112.4516610045.9913.0517210069.0414.0675510080.85 15.961510092.6319.26447
10099.3722.0305910104.5122.71455 10136.421.6017710175.7922.53262 10235.222.15852
10270.8422.8430710321.5926.76702 10425.337.3396910525.2944.8910810580.8248.29411
#Mann= 3 , 0 , 0
9300.079  0.0531       09300.079  0.0531       010580.82  0.0531       0
#XS Ineff= 2 , 0
       09722.543                       0
Bank Sta=9300.079,10580.82
Exp/Cntr=0.3,0.1

Type RM Length L Ch R = 1 , 9808.75,296.127900,296.127900,296.127900
XS GIS Cut Line= 6
865257.981236846852700.949792224865558.576745888852215.018757548
865658.276722835852108.220775251865710.820508114852022.491904978
865770.896142742851875.561390049865854.777239043851640.697460288
#Sta/Elev= 30
9452.43468.545399459.39164.961689482.77450.297559494.46644.346629517.84942.30436
9576.30840.692719581.78439.839389601.08532.21049 9658.1529.642279669.84127.99656
9704.91627.933739751.68325.365799810.84726.302699941.65421.914129953.545 19.5701
9965.37914.208589977.07610.175929988.7727.53498310012.177.161445 10023.97.838795
10050.0217.5280710065.2319.4525210106.9921.9109910149.6422.8160410279.0821.08979
10300.9622.5873610355.4329.15874 10398.231.7459310493.9932.8668110679.0742.61217
#Mann= 3 , 0 , 0
9452.434  0.0518       09452.434  0.0518       010679.07  0.0518       0
#XS Ineff= 2 , 0
       0 9790.45                       0
Bank Sta=9452.434,10679.07
Exp/Cntr=0.3,0.1

Type RM Length L Ch R = 1 ,9512.622,527.663700,527.663700,527.663700
XS GIS Cut Line= 3
865844.938434717853027.338635725865824.005890433851879.695596327
865864.235408531 851675.86777637
#Sta/Elev= 30
 9184.3652.257889226.70651.692959246.70969.110359256.71170.832369276.71463.52624
9326.72361.548379356.72850.615569386.73344.297899516.75437.176849556.76125.71129
9576.764 23.77889676.78121.582489706.78623.936559746.79320.519129796.80120.65638
9846.80924.776749876.814 18.06389896.81822.295819946.82623.796239956.82822.43605
9966.82917.346429976.8318.1108559986.833 6.5411210016.847.74245210036.8416.60321
10046.8417.7380610156.8619.4183410266.88 33.094910438.9134.5941310539.9539.38531
#Mann= 3 , 0 , 0
 9184.36  0.0497       0 9184.36  0.0497       010539.95  0.0497       0
#XS Ineff= 2 , 0
       09592.675                       0
Bank Sta=9184.36,10539.95
Exp/Cntr=0.3,0.1

Type RM Length L Ch R = 1 ,8984.959,724.411700,724.411700,724.411700
XS GIS Cut Line= 2
865871.246323801 853046.26489671866580.939549551851504.585159954
#Sta/Elev= 30
8924.11350.425638958.53249.13851 8969.5453.494838980.91865.131148991.55870.21743
9046.60167.28912 9057.6161.133329112.65348.249629200.72344.029829255.76627.23483
9288.79228.099599365.85319.874699442.91419.80039 9475.9423.28739    955319.37401
9597.03523.317149630.06119.791019817.92118.930619905.27823.917469961.40716.74331
 9971.3314.327529982.3395.6214119993.3485.18131210026.37 7.3848910037.3812.85163
10081.42 20.264910279.5718.8611310367.95 23.084910511.4444.35366 10621.367.59477
#Mann= 3 , 0 , 0
8924.113  0.0419       08924.113  0.0419       0 10621.3  0.0419       0
#XS Ineff= 2 , 0
       09271.675        10448.46       0
Bank Sta=8924.113,10621.3
Exp/Cntr=0.3,0.1