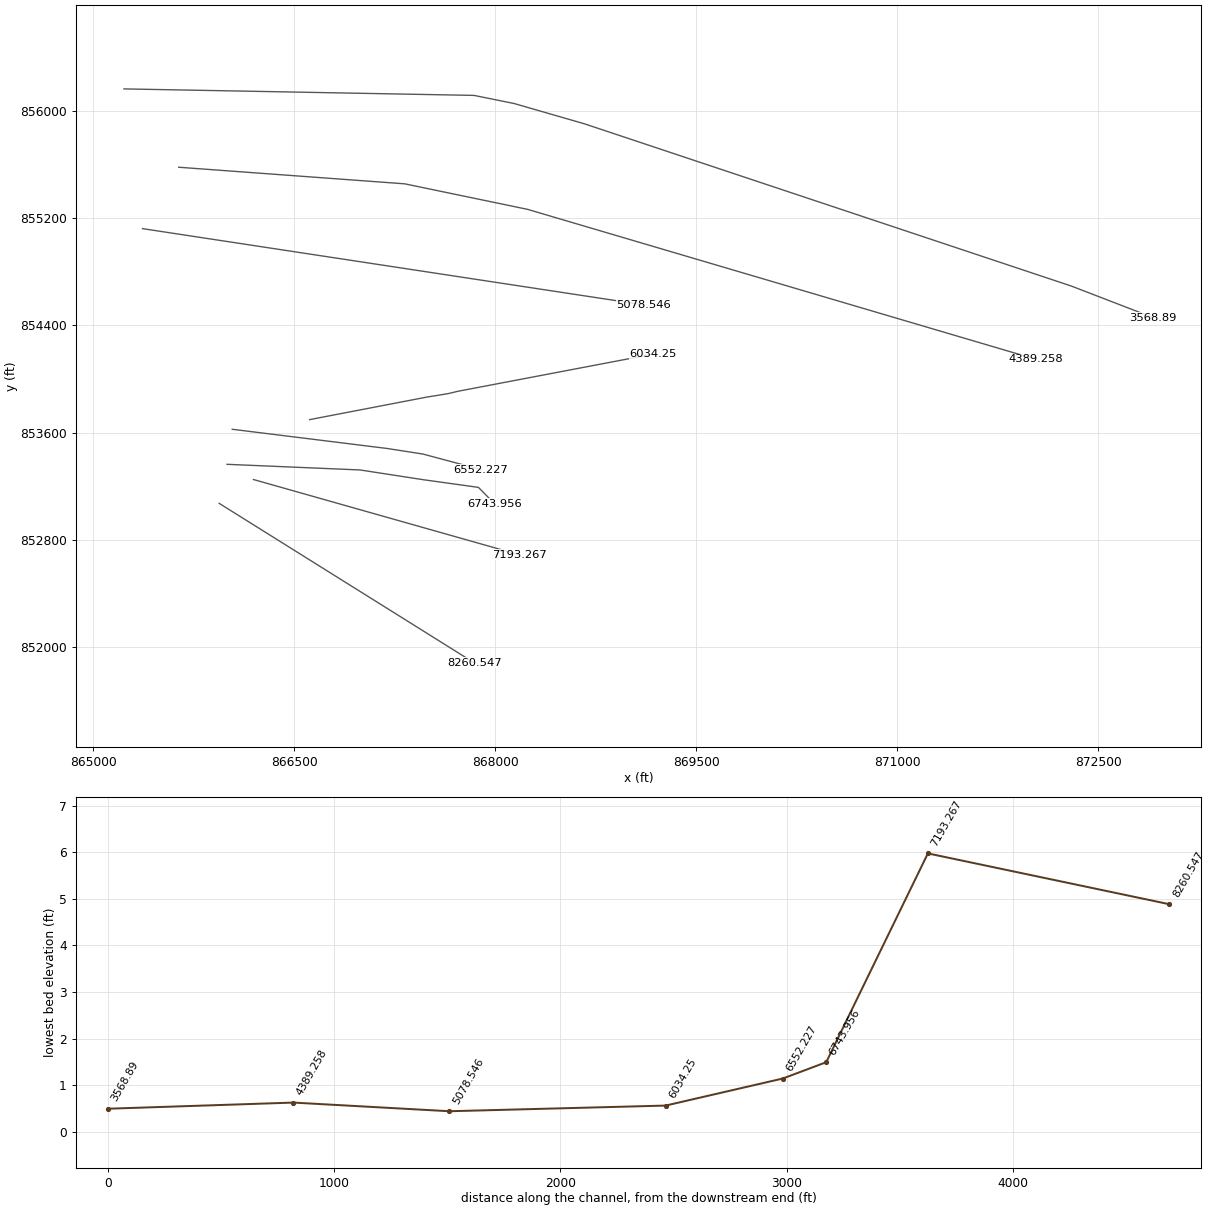
HEC-RAS study 16941_ras.prj: 16941

--- 16941_ras.g01 (geometry) --- (continued)

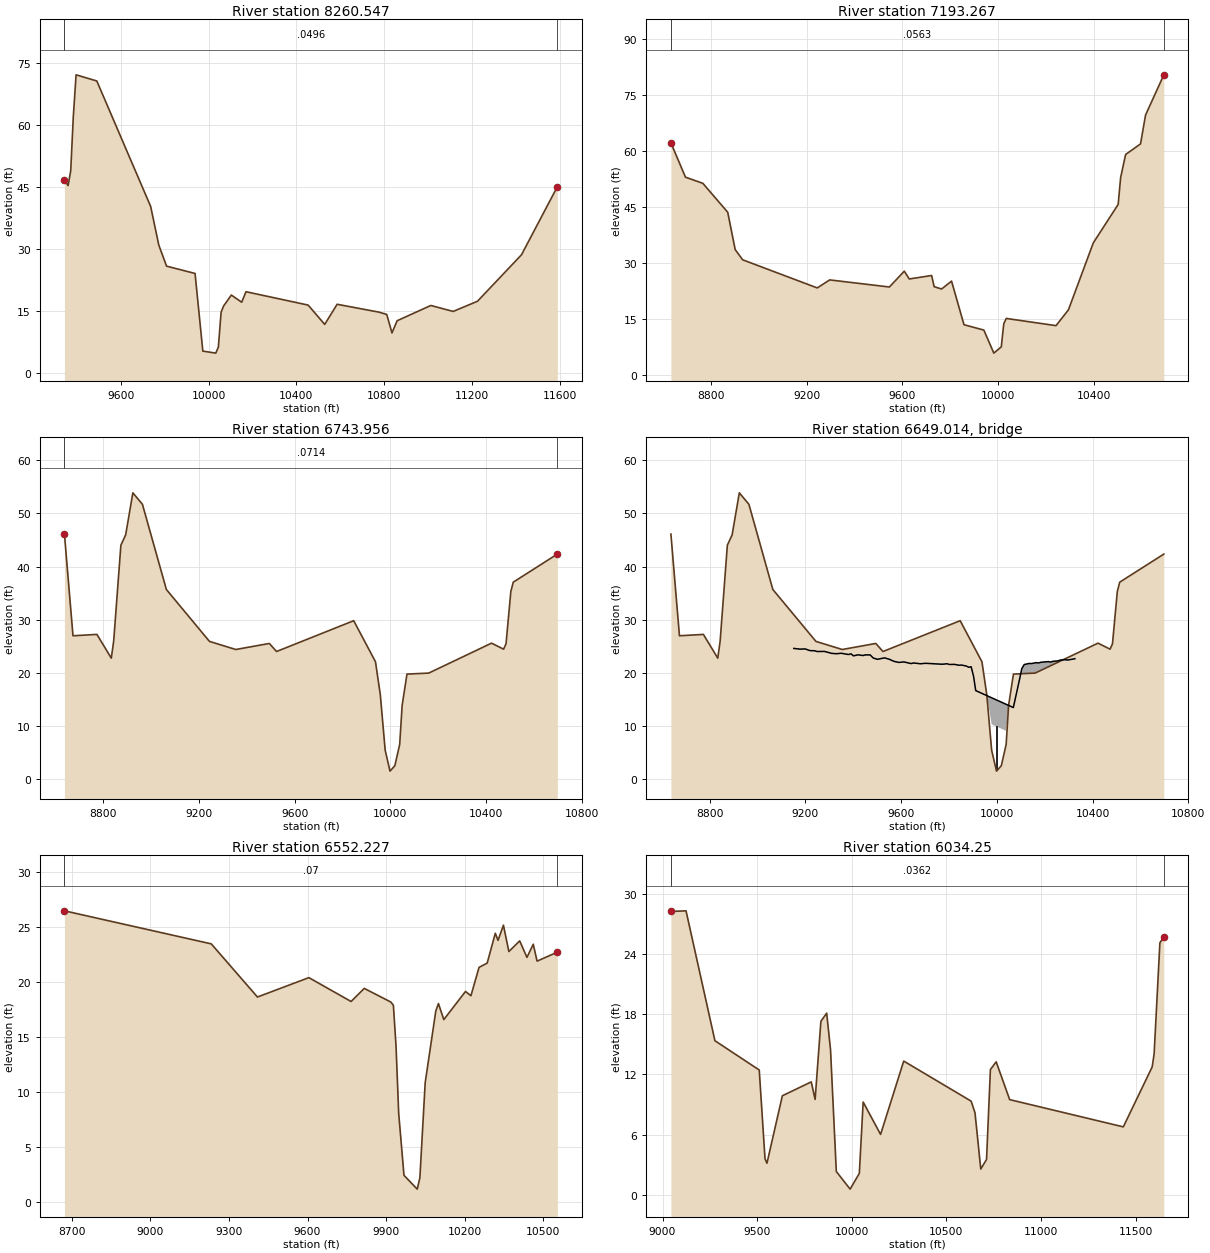
Type RM Length L Ch R = 1 ,8260.547,1067.279600,1067.279600,1067.279600
XS GIS Cut Line= 2
865940.791929916853073.115484697867843.425754303851883.529257981
#Sta/Elev= 30
 9344.1446.658919360.89645.33232 9372.6948.872949384.48461.933699397.17472.06059
9491.489 70.57759736.70740.284589773.67630.970929809.05725.880389938.78824.11274
9974.1695.37038510033.144.88418210044.936.37394810057.3814.7822410068.5216.24178
 10103.9 18.901710151.0717.1723410170.5519.70422 10453.516.4820610528.9511.82275
10585.5416.6770910776.1414.7752910811.5214.2153310835.119.761371 10858.712.70394
11012.0116.38715 11113.714.94894 11224.317.4000411424.7928.6258711588.0545.06144
#Mann= 3 , 0 , 0
 9344.14  0.0496       0 9344.14  0.0496       011588.05  0.0496       0
#XS Ineff= 2 , 0
       0 9744.98        11077.46       0
Bank Sta=9344.14,11588.05
Exp/Cntr=0.3,0.1

Type RM Length L Ch R = 1 ,7193.267,449.311100,449.311100,449.311100
XS GIS Cut Line= 2
866196.491008876853250.886785651868178.610198398852689.835610714
#Sta/Elev= 30
8632.64162.170168693.44952.988528766.19951.342288870.12843.617658901.30633.63576
8932.48530.911429244.27223.395419296.23625.537269545.66523.643629608.02327.87238
9628.80825.787579722.344 26.71519732.73723.737619763.916 23.10259805.48725.21645
9857.45213.571079940.59512.126579982.1665.97571410013.357.65347810023.7413.82762
10034.1315.2433410241.9913.3195410293.9517.5341510397.8835.4325410501.8145.70478
 10512.252.9121210532.9959.0439910595.3561.8789310616.1369.5644410692.6380.32971
#Mann= 3 , 0 , 0
8632.641  0.0563       08632.641  0.0563       010692.63  0.0563       0
#XS Ineff= 2 , 0
       0 9520.64        10283.33       0
Bank Sta=8632.641,10692.63
Exp/Cntr=0.3,0.1

Type RM Length L Ch R = 1 ,6743.956,191.729300,191.729300,191.729300
XS GIS Cut Line= 5
865999.273631226853364.276987946866991.678308494853322.226881077
867460.545013912853249.861955598867874.833412268853192.266795827
867997.286846538853068.066597169
#Sta/Elev= 30
8637.62246.114738673.38126.97003 8773.4727.226128833.52422.757098843.53326.00232
 8873.5644.015748893.57845.966978923.60553.878738963.64151.720019063.73135.68317
9243.89225.909569353.99124.385669494.11625.525739524.14324.006669846.76529.80715
 9937.8322.072159958.06715.835699978.304 5.418999998.541   1.49110018.782.512672
10039.016.52899710049.1313.8378510069.3719.7563710160.3119.9452310422.8125.58167
 10473.324.4513710483.3925.4565710503.5835.3051110513.6837.0603610698.0242.34755
#Mann= 3 , 0 , 0
8637.622  0.0714       08637.622  0.0714       010698.02  0.0714       0
#XS Ineff= 2 , 0
       09919.473         10075.5       0
Bank Sta=8637.622,10698.02
Exp/Cntr=0.3,0.1

Type RM Length L Ch R = 3 ,6649.014,,,
BEGIN DESCRIPTION:
END DESCRIPTION:
Bridge Culvert--1,0,-1,-1, 0
Deck Dist Width WeirC Skew NumUp NumDn MinLoCord MaxHiCord MaxSubmerge Is_Ogee
48.864650,94.000000,2.6,0, 60, 60, , , 0.95, 0, 0,0,,
 9151.29 9178.28 9198.43 9218.58 9238.72 9248.80 9279.02 9309.25 9329.40 9349.55
 9379.77 9389.85 9400.86 9420.07 9440.22 9450.30 9470.45 9483.01 9500.67 9530.83
 9550.93 9571.02 9591.12 9611.21 9641.36 9651.41 9681.55 9701.65 9771.98 9792.08
 9802.13 9822.23 9842.32 9852.37 9872.47 9882.53 9892.61 9902.68 9911.71 9914.16
 9914.1610068.9510080.1610080.1610094.1610104.2410114.3110134.4710144.5410164.68
10174.7510184.8110215.0210225.0910235.1610255.3010265.3710285.5010295.5710326.33
   24.59   24.45   24.50   24.18   24.15   24.00   24.03   23.66   23.59   23.68
   23.44   23.58   23.19   23.39   23.25   23.37   23.37   22.79   22.54   22.81
   22.54   22.14   21.95   22.05   21.74   21.85   21.70   21.79   21.61   21.70
   21.56   21.59   21.42   21.46   21.27   21.04   21.14   19.35   16.65   16.60
   16.60   13.46   15.75   15.75   18.61   20.78   21.55   21.76   21.74   21.91
   21.86   21.99   22.11   22.03   22.17   22.24   22.40   22.47   22.40   22.65
 -975.41 -975.55 -975.50 -975.82 -975.85 -976.00 -975.97 -976.34 -976.41 -976.32
 -976.56 -976.42 -976.81 -976.61 -976.75 -976.63 -976.63 -977.21 -977.46 -977.19
 -977.46 -977.86 -978.05 -977.95 -978.26 -978.15 -978.30 -978.21 -978.39 -978.30
 -978.44 -978.41 -978.58 -978.54 -978.73 -978.96 -978.86 -980.65 -983.35 -983.40
   11.60    8.46   10.75 -984.25 -981.39 -979.22 -978.45 -978.24 -978.26 -978.09
 -978.14 -978.01 -977.89 -977.97 -977.83 -977.76 -977.60 -977.53 -977.60 -977.35
 9151.29 9178.28 9198.43 9218.58 9238.72 9248.80 9279.02 9309.25 9329.40 9349.55
 9379.77 9389.85 9400.86 9420.07 9440.22 9450.30 9470.45 9483.01 9500.67 9530.83
 9550.93 9571.02 9591.12 9611.21 9641.36 9651.41 9681.55 9701.65 9771.98 9792.08
 9802.13 9822.23 9842.32 9852.37 9872.47 9882.53 9892.61 9902.68 9910.95 9910.95
 9911.7110068.9510076.9510076.9510094.1610104.2410114.3110134.4710144.5410164.68
10174.7510184.8110215.0210225.0910235.1610255.3010265.3710285.5010295.5710326.33
   24.59   24.45   24.50   24.18   24.15   24.00   24.03   23.66   23.59   23.68
   23.44   23.58   23.19   23.39   23.25   23.37   23.37   22.79   22.54   22.81
   22.54   22.14   21.95   22.05   21.74   21.85   21.70   21.79   21.61   21.70
   21.56   21.59   21.42   21.46   21.27   21.04   21.14   19.35   16.88   16.88
   16.65   13.46   15.09   15.09   18.61   20.78   21.55   21.76   21.74   21.91
   21.86   21.99   22.11   22.03   22.17   22.24   22.40   22.47   22.40   22.65
 -975.41 -975.55 -975.50 -975.82 -975.85 -976.00 -975.97 -976.34 -976.41 -976.32
 -976.56 -976.42 -976.81 -976.61 -976.75 -976.63 -976.63 -977.21 -977.46 -977.19
 -977.46 -977.86 -978.05 -977.95 -978.26 -978.15 -978.30 -978.21 -978.39 -978.30
 -978.44 -978.41 -978.58 -978.54 -978.73 -978.96 -978.86 -980.65 -983.12   11.88
   11.65    8.46   10.09 -984.91 -981.39 -979.22 -978.45 -978.24 -978.26 -978.09
 -978.14 -978.01 -977.89 -977.97 -977.83 -977.76 -977.60 -977.53 -977.60 -977.35
Pier Skew, UpSta & Num, DnSta & Num=  ,9997.16, 2 ,9993.95, 2 , 0 , 0 , 0 ,,
    4.00    4.00
 -985.08   14.92
    4.00    4.00
 -985.02   14.98
BR Coef=-1 , 0 , 0 ,, 0 ,,,0.8,0,1,0,
WSPro=,,,, 1 ,,,, 0 ,,,, 0 ,,,,-1 ,-1 ,-1 , 0 , 0 , 0 , 0 , 0
BC Design=,, 0 ,, 0 ,,,,,,

Type RM Length L Ch R = 1 ,6552.227,517.976900,517.976900,517.976900
XS GIS Cut Line= 4
866038.403601737853625.702040035867191.400048664853482.774198809
867459.723509675 853441.09673467867893.983439771853325.002750242
#Sta/Elev= 30
 8671.3526.449249232.20623.444189408.64218.610569605.03820.374079766.26318.20419
9816.64619.394189917.77418.158719927.89317.862259938.01314.146759948.133 8.03549
9968.3732.39500410018.971.14069410029.092.17771110049.3310.8179710089.8117.32775
10099.9318.0180310120.5316.5588310203.3319.1162910224.0418.7251510255.0921.30843
10286.1421.69426 10317.224.4103210327.5523.7603310348.2525.1420410368.9522.74774
10410.3623.7157210438.0722.2158410462.1123.4105910476.7921.8752810554.2222.68919
#Mann= 3 , 0 , 0
 8671.35    0.07       0 8671.35    0.07       010554.22    0.07       0
#XS Ineff= 2 , 0
       09913.652        10075.12       0
Bank Sta=8671.35,10554.22
Exp/Cntr=0.3,0.1

Type RM Length L Ch R = 1 , 6034.25,955.703900,955.703900,955.703900
XS GIS Cut Line= 6
866616.511480782853697.821702119867490.447257009853865.896761846
867569.456143513853878.595529851867647.381713123853891.341649476
867720.216529068853908.831692277869175.376013224854185.858308179
#Sta/Elev= 30
9044.25328.22769 9124.1828.290959276.92915.347189511.14412.428969541.6943.580674
9551.877 3.137329633.3439.8629119786.09211.245149806.4589.5000669837.00817.27897
9867.55818.097859887.92414.448229918.4742.3180579991.3630.55937810040.112.130908
10060.389.23516210152.456.01013510274.7613.3198810631.059.32593210651.41 8.17158
10681.94 2.5624910712.483.51790310732.8412.4721710763.3813.2460610834.64  9.4785
11435.23 6.7623411587.9312.7433711598.1114.0403611628.6525.1107611649.3925.67371
#Mann= 3 , 0 , 0
9044.253  0.0362       09044.253  0.0362       011649.39  0.0362       0
#XS Ineff= 2 , 0
       09869.601        10283.14       0
Bank Sta=9044.253,11649.39
Exp/Cntr=0.3,0.1

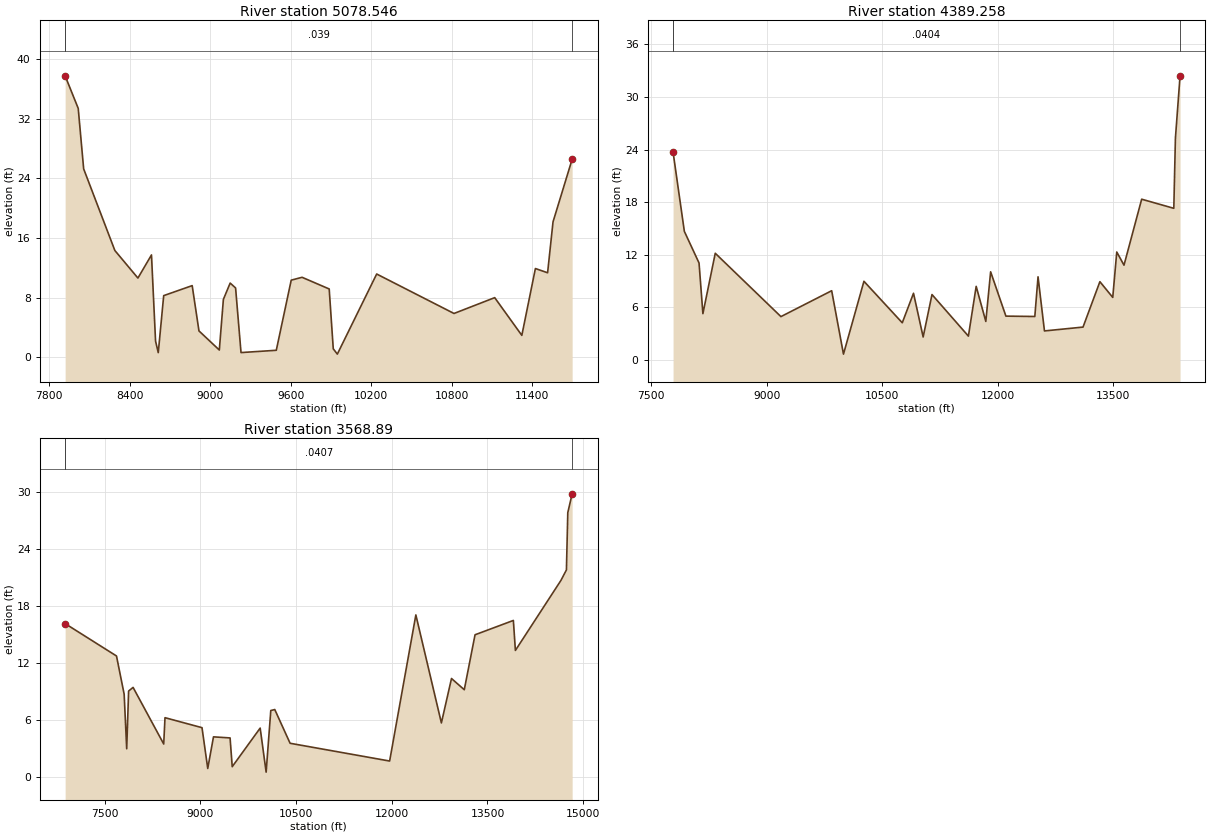
Type RM Length L Ch R = 1 ,5078.546,689.287700,689.287700,689.287700
XS GIS Cut Line= 2
865368.496609828855122.516785066 869105.94955722854554.214309323
#Sta/Elev= 30
 7918.5737.748338016.18233.378948056.64225.274658289.28614.32943 8461.2410.63464
8562.38913.738198592.7342.1775368612.9640.6376848653.4248.2794378865.8389.622883
8916.4123.5504579068.1370.9880789098.4817.7791399149.0569.9627579189.5169.309191
9229.9760.6458939492.9640.9521119604.229  10.3539685.14810.738399887.4479.172389
9917.7921.1499359948.1370.43775210241.4711.1778210818.025.88739811121.478.009642
11323.772.95222211424.9211.9120111515.9511.3452811556.4118.1716311698.9826.56328
#Mann= 3 , 0 , 0
 7918.57   0.039       0 7918.57   0.039       011698.98   0.039       0
#XS Ineff= 2 , 0
       09781.899        10284.42       0
Bank Sta=7918.57,11698.98
Exp/Cntr=0.3,0.1

Type RM Length L Ch R = 1 ,4389.258,820.367800,820.367800,820.367800
XS GIS Cut Line= 4
 865638.67424292855580.463366559867325.323199156855456.624805147
868241.174264175855266.271023031872032.864853607854147.940078429
#Sta/Elev= 30
7785.27823.718727931.99814.646348122.50911.035078172.6445.2484018333.07412.14454
9185.3624.9094899843.8317.8671449997.0360.62363310262.598.94327510759.934.203513
 10905.97.57563811031.012.58469411145.697.42836711618.252.68099311719.128.363872
11844.234.35879111906.7810.0285412104.874.96466412480.214.92330212521.919.457238
12605.323.27293313105.76 3.71243 13324.78.89911713491.527.10285113543.6512.29177
13637.4810.7850113866.8518.3223314283.8817.2814614304.7625.2820614365.0632.41686
#Mann= 3 , 0 , 0
7785.278  0.0404       07785.278  0.0404       014365.06  0.0404       0
#XS Ineff= 2 , 0
       09141.916        10850.61       0
Bank Sta=7785.278,14365.06
Exp/Cntr=0.3,0.1

Type RM Length L Ch R = 1 , 3568.89,0.000000,0.000000,0.000000
XS GIS Cut Line= 6
865230.221540396 856164.83861542867841.910685406 856116.31284825
868140.825204689 856055.88034859 868666.65629129855904.063361352
872298.139227581854693.944353685872908.743010627854458.491565507
#Sta/Elev= 30
 6880.7916.140277685.70812.728337805.7298.7040857845.7352.9537057875.7419.034962
7945.7539.4182768425.8363.4549128445.8396.2273189025.9395.1760769115.9550.876371
 9205.974.2078839466.0154.0944319499.5551.0643979937.5485.13250910031.220.491499
10104.086.98109510166.537.086727 10406.73.53125911966.711.65978412377.7917.05502
12777.875.67464112936.4410.3563913136.719.17345113305.3614.9637513906.1816.47292
 13937.8 13.314414651.9320.6943514737.6821.7985314759.1127.8339814827.4329.81448
#Mann= 3 , 0 , 0
 6880.79  0.0407       0 6880.79  0.0407       014827.43  0.0407       0
#XS Ineff= 2 , 0
       08417.888        11452.41       0
Bank Sta=6880.79,14827.43
Exp/Cntr=0.3,0.1